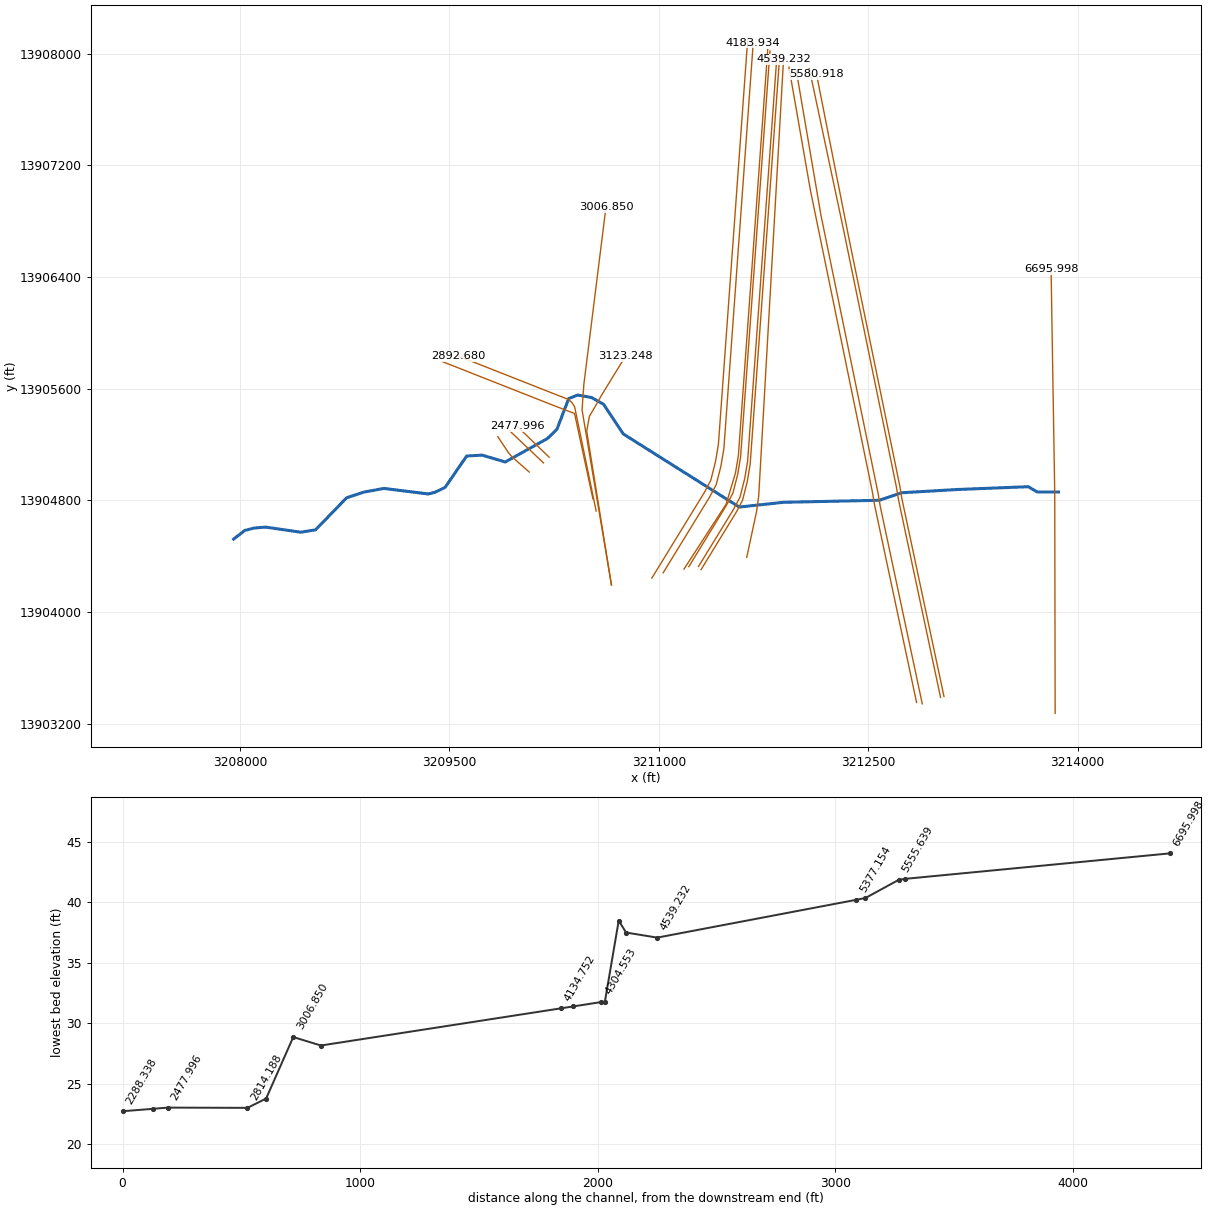
--- R102-03-00.prj (project) ---

Proj Title=R102-03-00
Current Plan=p04
Default Exp/Contr=.3,.1
English Units
Geom File=g03
Flow File=f02
Flow File=f05
Plan File=p02
Plan File=p04
Y Axis Title=Elevation
X Axis Title(PF)=Main Channel Distance
X Axis Title(XS)=Station
BEGIN DESCRIPTION:
Jackson Bayou Watershed
Tributary 2.7 to Gum Gully
HCFCD Unit R102-03-00 & R102-03-01
Flood Hazard / Floodway Model
10, 2, 1, 0.2% Event
Filename r1020300.prj
Prepared by:  FTN Associates Ltd.   DATE:  April 2003
Reviewed by: 	 DATE:
STATUS (Final)
Normal depth calculated between sections 443s2u and 443v1 at RS 704.003 and 102.649 respectively with inverts 16.9 and 14.32. Normal depth calculated to be 0.00429
END DESCRIPTION:
DSS Export Rating Curves= 0
DSS Export Rating Curve Sorted= 0
DSS Export Volume Flow Curves= 0
DXF OffsetX= 0
DXF OffsetY= 0
DXF ScaleX= 1
DXF ScaleY= 10

--- R102-03-00.p04 (plan) ---

Plan Title=Floodway
Version=Version 3.0.1  Mar 2001
Short Identifier=Floodway0607
Geom File=g03
Flow File=f05
Subcritical Flow
K Sum by GR= 0
Std Step Tol= 0.01
Critical Tol= 0.01
Num of Std Step Trials= 20
Max Error Tol= 0.3
Flow Tol Ratio= 0.001
Split Flow NTrial= 30
Split Flow Tol= 0.02
Split Flow Ratio= 0.02
Log Output Level= 0
Friction Slope Method= 1
Unsteady Friction Slope Method= 2
Parabolic Critical Depth
Global Vel Dist= 0 , 0 , 0
Global Log Level= 0
CheckData=True
Encroach Param=-1 ,0,0, 2
Encroach River=R102-03-00
Encroach Reach=Gum Gully 2.7
Encroach Node=6695.998
       1     525    1325
Encroach Node=5580.918
       1 1467.17 1516.59
Encroach Node=5555.639
       1    1472    1539
Encroach Node=5485.8
       1 1481.27    1535
Encroach Node=5415.974
       1    1480    1530
Encroach Node=5377.154
       1 1459.04 1498.35
Encroach Node=4539.232
       1  354.32   390.4
Encroach Node=4407.930
       1  503.68  551.74
Encroach Node=4377.126
       1  496.61  542.56
Encroach Node=4352
       1  496.61  542.56
Encroach Node=4318.626
       1  504.98     545
Encroach Node=4304.553
       1  504.98  556.64
Encroach Node=4244.24
       1  504.98  560.19
Encroach Node=4183.934
       1  508.53  560.19
Encroach Node=4134.752
       1  504.77  556.43
Encroach Node=3123.248
       1     198     258
Encroach Node=3006.850
       1     220     285
Encroach Node=2948
       1     220     285
Encroach Node=2892.680
       1     790     842
Encroach Node=2814.188
       1   841.8  883.79
Encroach Node=2477.996
       1  111.43   158.9
Encroach Node=2416.539
       1     120     175
Encroach Node=2352.44
       1     120     175
Encroach Node=2288.338
       1     135     175
Encroach Node=2230.781
       1  125.99  172.86
Encroach Node=1366.401
       1      50      95
Encroach Node=1323.830
       1     174     216
Encroach Node=1303
       1   184.5     205
Encroach Node=1255.123
       1     170     205
Encroach Node=1214.004
       1  184.95  214.26
Encroach Node=704.003
       1  191.56   257.5
Encroach Node=647.875
       1  162.18  209.32
Encroach Node=599.59
       1  162.18     212
Encroach Node=551.306
       1     165     212
Encroach Node=506.543
       1     176     226
Encroach Node=229.844
       1  412.78  464.67
Encroach Node=207.051
       1     458     488
Encroach Node=185
       1   461.5   478.5
Encroach Node=150.502
       1     450     485
Encroach Node=102.649
       1   461.2   497.9
Encroach Reach=R102-03-00_0001
Encroach Node=6695.998
       1     525    1325
Encroach Node=5580.918
       1 1467.17 1516.59
Encroach Node=5555.639
       1    1472    1539
Encroach Node=5485.8
       1 1481.27    1535
Encroach Node=5415.974
       1    1480    1530
Encroach Node=5377.154
       1 1459.04 1498.35
Encroach Node=4539.232
       1  354.32   390.4
Encroach Node=4407.930
       1  503.68  551.74
Encroach Node=4377.126
       1  496.61  542.56
Encroach Node=4352
       1  496.61  542.56
Encroach Node=4318.626
       1  504.98     545
Encroach Node=4304.553
       1  504.98  556.64
Encroach Node=4244.24
       1  504.98  560.19
Encroach Node=4183.934
       1  508.53  560.19
Encroach Node=4134.752
       1  504.77  556.43
Encroach Node=3123.248
       1     198     258
Encroach Node=3006.850
       1     220     285
Encroach Node=2948
       1     220     285
Encroach Node=2892.680
       1     790     842
Encroach Node=2814.188
       1   841.8  883.79
Encroach Node=2477.996
       1  111.43   158.9
Encroach Node=2416.539
       1     120     175
Encroach Node=2352.44
       1     120     175
Encroach Node=2288.338
       1     135     175
Encroach Node=2230.781
       1  125.99  172.86
Encroach Node=1366.401
       1      50      95
Encroach Node=1323.830
       1     174     216
Encroach Node=1303
       1   184.5     205
Encroach Node=1255.123
       1     170     205
Encroach Node=1214.004
       1  184.95  214.26
Encroach Node=704.003
       1  191.56   257.5
Encroach Node=647.875
       1  162.18  209.32
Encroach Node=599.59
       1  162.18     212
Encroach Node=551.306
       1     165     212
Encroach Node=506.543
       1     176     226
Encroach Node=229.844
       1  412.78  464.67
Encroach Node=207.051
       1     458     488
Encroach Node=185
       1   461.5   478.5
Encroach Node=150.502
       1     450     485
Encroach Node=102.649
       1   461.2   497.9
Computation Interval=1HOUR
Output Interval=1HOUR
Run HTab= 0
Run UNet= 0
Run PostProcess= 0
UNET Theta= 1
UNET ZTol= 0.02
UNET ZSATol= 0.1
UNET MxIter= 20
UNET MaxInSteps= 20
UNET DtIC= 0
UNET DtMin= 0
UNET MaxCRTS= 20
UNET WFStab= 2
UNET SFStab= 1
UNET WFX= 1
UNET SFX= 1
UNET Convert EG Bridges=-1
UNET Use Existing IB Tables=-1
Instantaneous Interval=1HOUR
Write IC File= 0
Write Velocity= 0
Write Detailed= 0

--- R102-03-00.p02 (plan) ---

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Plan Title=FEMA Effective June 2007
Short Identifier=FEMAeff0607
Geom File=g03
Flow File=f02
Encroach Param=-1 ,0,0, 0

--- R102-03-00.f05 (steady flow) ---

Flow Title=Floodway
Version=Version 3.0.1  Mar 2001
Number of Profiles= 2
Profile Names=1PCT_100yr,1PCTFloodway_100yrFW
River Rch & RM=R102-03-00,R102-03-00_0001    ,6695.998
     820     820
River Rch & RM=R102-03-00,R102-03-00_0001    ,5580.918
     860     860
River Rch & RM=R102-03-00,R102-03-00_0001    ,4539.232
     877     877
River Rch & RM=R102-03-00,R102-03-00_0001    ,4134.752
     918     918
River Rch & RM=R102-03-00,R102-03-00_0001    ,3123.248
     928     928
River Rch & RM=R102-03-00,R102-03-00_0001    ,2892.680
    1574    1574
Boundary for River Rch & Prof#=R102-03-00,R102-03-00_0001    , 1
Up Type= 0
Dn Type= 3
Dn Slope=.00429
Boundary for River Rch & Prof#=R102-03-00,R102-03-00_0001    , 2
Up Type= 0
Dn Type= 3
Dn Slope=.00429
DSS Import GetInterval= 0
DSS Import GetPeak= 0
DSS Import FillOption= 0

--- R102-03-00.f02 (steady flow) ---

Flow Title=FEMA Effective June 2007
Version=Version 3.0.1  Mar 2001
Number of Profiles= 4
Profile Names=10PCT_10yr,2PCT_50yr,1PCT_100yr,0.2PCT_500yr
River Rch & RM=R102-03-00,R102-03-00_0001    ,6695.998
     483     704     820    1232
River Rch & RM=R102-03-00,R102-03-00_0001    ,5580.918
     524     744     860    1348
River Rch & RM=R102-03-00,R102-03-00_0001    ,4539.232
     541     760     877    1396
River Rch & RM=R102-03-00,R102-03-00_0001    ,4134.752
     586     801     918    1523
River Rch & RM=R102-03-00,R102-03-00_0001    ,3123.248
     597     811     928    1554
River Rch & RM=R102-03-00,R102-03-00_0001    ,2892.680
    1003    1394    1574    2529
Boundary for River Rch & Prof#=R102-03-00,R102-03-00_0001    , 1
Up Type= 0
Dn Type= 3
Dn Slope=.00429
Boundary for River Rch & Prof#=R102-03-00,R102-03-00_0001    , 2
Up Type= 0
Dn Type= 3
Dn Slope=.00429
Boundary for River Rch & Prof#=R102-03-00,R102-03-00_0001    , 3
Up Type= 0
Dn Type= 3
Dn Slope=.00429
Boundary for River Rch & Prof#=R102-03-00,R102-03-00_0001    , 4
Up Type= 0
Dn Type= 3
Dn Slope=.00429
DSS Import GetInterval= 0
DSS Import GetPeak= 0
DSS Import FillOption= 0

--- R102-03-00.g03 (geometry) ---

Geom Title=R102-03-00 June 2007
Version=Version 3.0.1  Mar 2001

River Reach=R102-03-00      ,R102-03-00_0001
Reach XY= 30
     3213862.984    13904860.511     3213710.944    13904860.511
     3213646.161    13904898.283     3213138.199    13904878.219
     3212741.377     13904855.07     3212579.327    13904801.053
     3211893.791    13904786.628     3211576.378    13904752.533
     3210745.114    13905276.635     3210605.547    13905488.188
     3210518.519    13905536.983     3210419.599    13905554.787
     3210355.097    13905529.126     3210271.421    13905311.136
     3210203.033    13905243.359     3209900.367    13905075.365
     3209735.312    13905124.291     3209624.172    13905117.969
     3209469.914    13904893.193     3209396.458    13904857.934
     3209349.446    13904846.181     3209032.115    13904885.848
     3208889.627    13904859.901     3208764.454     13904818.99
     3208542.195    13904589.404      3208435.95    13904572.307
     3208184.381    13904608.943      3208101.34    13904602.226
      3208034.58    13904584.677     3207955.247    13904522.974

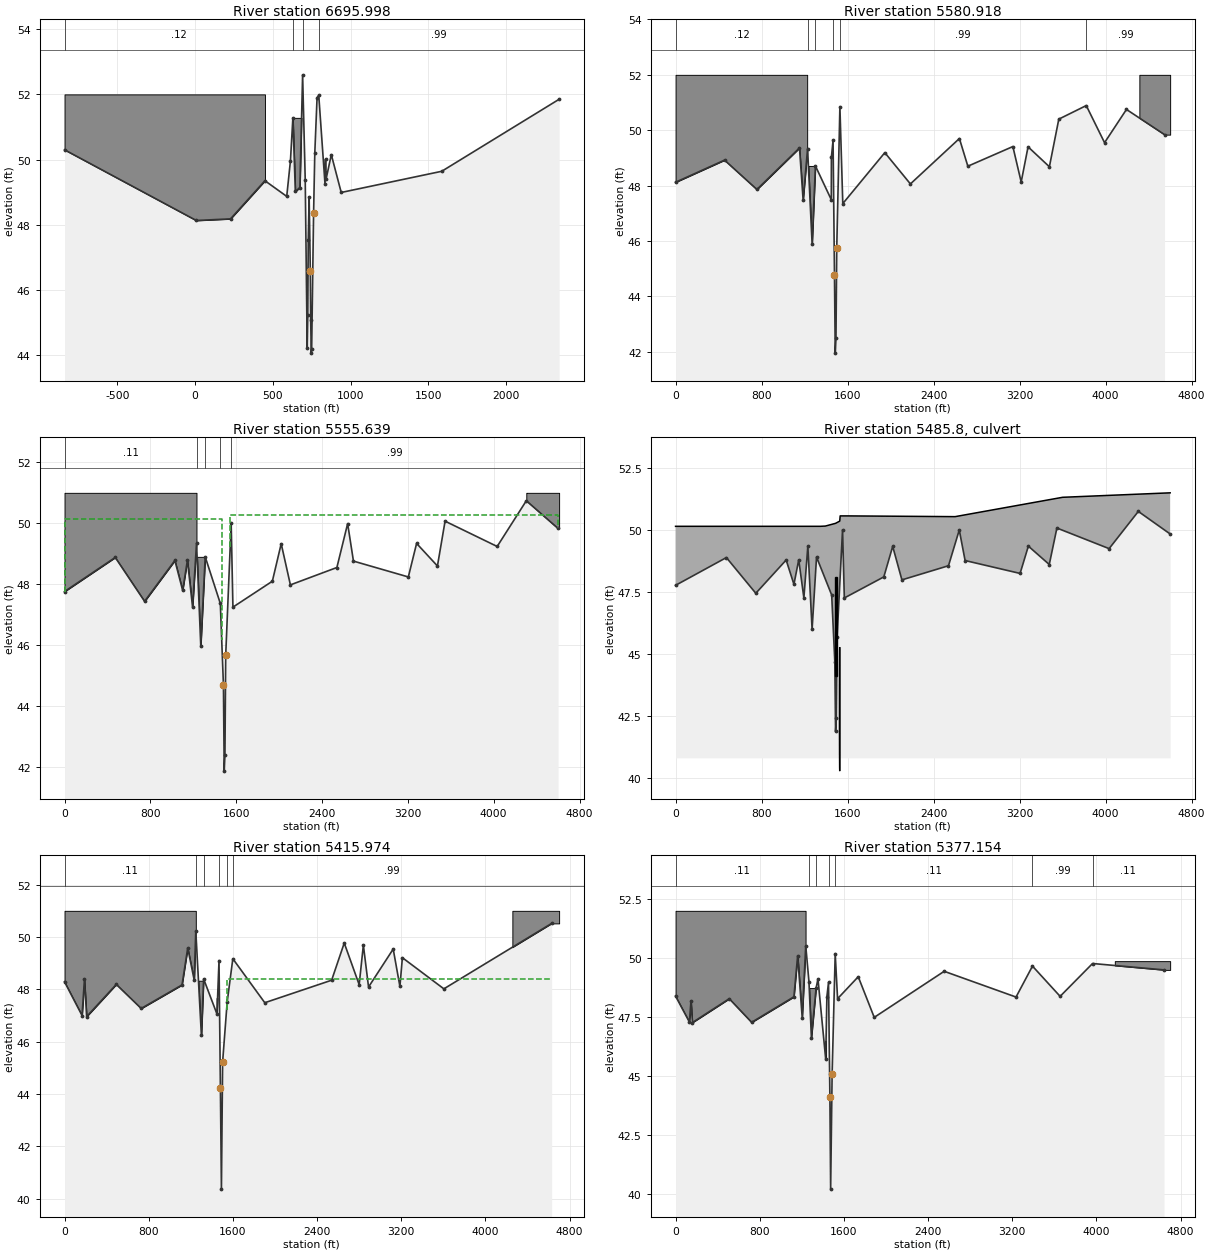
Type RM Length L Ch R = 1 ,6695.998,1100.2,1115.08,1145.86
BEGIN DESCRIPTION:
443v5
Bank Station offset =      4253
LOB blocked to close -- watershed divide, anticipate flows for 1% chance can be effective on near LOB based on WSELS and ground elev.
LOB adjacent to stream is a canal
Adjusted Manning's values at this location to remove a crossing profile.  Set n = 0.99 in ROB as flows are ineffective in this area.
END DESCRIPTION:
XS GIS Cut Line= 6
 3213839.119006813903274.8104025     3213837.584    13904114.809
     3213836.316    13904808.694     3213835.458    13904894.271
     3213822.313    13905699.994 3213810.002055813906454.5935342
#Sta/Elev= 30
    -840    50.3    7.28   48.13  227.44   48.18  448.59   49.35  588.68   48.87
  612.52   49.96  628.22   51.28  643.96   49.02  673.22   49.14  690.78    52.6
  707.61   49.38  720.36   44.22  724.01   45.22  727.07   47.53  732.82   48.86
  740.33   46.58  742.65   45.09  746.53   44.06  749.02   44.19  761.39   48.36
  769.07   50.19  783.68    51.9  794.56   51.97  834.92   49.24  838.24   50.01
  841.66    49.4  875.29   50.15     939   48.99  1585.3   49.64    2340   51.85
#Mann= 4 ,-1 , 0
    -840     .12       0  628.22     .01       0  690.78     .05       0
  794.56     .99       0
#Block Obstruct= 3 ,-1
    -840  448.59      52                          628.22     685   51.28
Bank Sta=740.33,761.39
XS Rating Curve= 0
Exp/Cntr=.3,.1

Type RM Length L Ch R = 1 ,5580.918,25.28,25.28,26.18
BEGIN DESCRIPTION:
443s7u
xsec 4/4
Bank Station offset =      3515
ROB & LOB blocked to close -- watershed divide
LOB adjacent to stream is a canal. Anticipate flows for 1% chance can be effective on near LOB based on WSELS and ground Elev.
Adjusted Manning's values at this location to remove a crossing profile.  Set n = 0.99 in ROB as flows are ineffective in this area.
END DESCRIPTION:
XS GIS Cut Line= 5
     3213042.929      13903395.7     3212741.505    13904812.483
     3212726.687    13904902.323     3212367.601    13906650.055
     3212130.354    13907851.014
#Sta/Elev= 30
       0   48.12   455.6   48.92  756.49   47.86 1152.63   49.36 1186.47   47.48
 1227.95   49.33 1270.14   45.89 1300.81   48.71 1448.49   47.49  1449.3   49.02
 1464.87   49.63 1478.09   44.76 1485.13   41.95 1492.02   42.48 1499.21   45.76
 1528.48   50.85  1555.4   47.35 1946.26   49.19  2184.2   48.06 2639.88    49.7
  2718.5    48.7 3137.13   49.41 3214.53   48.13 3278.48    49.4 3476.83   48.68
 3564.42    50.4 3819.77   50.89 3989.88   49.55 4193.57   50.75 4547.95   49.84
#Mann= 6 ,-1 , 0
       0     .12       0 1227.95     .01       0 1300.81     .12       0
 1464.87     .05       0 1528.48     .99       0 3819.77     .99       0
#Block Obstruct= 3 ,-1
       0 1224.13      52 4313.59    4600      52    1235 1300.81   48.71
Bank Sta=1478.09,1499.21
XS Rating Curve= 0
Exp/Cntr=.5,.3

Type RM Length L Ch R = 1 ,5555.639,138.39,139.66,145.63
BEGIN DESCRIPTION:
copy of 443s7u - inverts adjusted based on slope between 443v4 and 443v5
xsec 3/4
Bank Station offset =      3512
ROB & LOB blocked to close -- watershed divide
LOB adjacent to stream is a canal
Adjusted Manning's values at this location to remove a crossing profile.  Set n = 0.99 in ROB as flows are ineffective in this area.  Edited geometry of near overbanks, removing survey points from narrower u/s copied survey section.  Verified using contour data from LIDAR.
END DESCRIPTION:
XS GIS Cut Line= 5
     3213018.324    13903389.549     3212716.901    13904806.332
     3212702.082    13904896.172     3212324.857    13906732.187
     3212078.276    13907892.677
#Sta/Elev= 30
       0   47.76   472.8   48.88  746.35   47.44 1028.69   48.78 1101.08    47.8
 1145.62   48.79 1193.57   47.25 1230.42   49.34 1270.01   45.98 1311.33    48.9
 1452.12   47.37  1481.3   44.68 1488.34   41.87 1495.23    42.4 1502.42   45.68
 1553.29      50  1569.7   47.25 1937.11    48.1 2019.62   49.33 2105.27   47.98
  2538.6   48.55  2638.9   49.99 2692.99   48.76 3204.59   48.24  3281.5   49.34
 3475.86    48.6 3546.99   50.07 4032.54   49.24 4304.22   50.74 4600.31   49.83
#Mann= 5 ,-1 , 0
       0     .11       0 1230.42     .01       0 1311.33     .11       0
 1452.12     .05       0 1553.29     .99       0
#XS Ineff= 2 , 0
       0    1465   50.14    1544       0   50.26
Permanent Ineff=
       F       F
#Block Obstruct= 3 ,-1
       0    1230      51    4304    4610      51    1235 1311.33    48.9
Bank Sta=1481.3,1502.42
XS Rating Curve= 0
Exp/Cntr=.5,.3

Type RM Length L Ch R = 2 ,5485.8  ,,,
BEGIN DESCRIPTION:
443s7;  FM 2100
END DESCRIPTION:
Bridge Culvert--1,0,-1,-1, 0
Deck Dist Width WeirC Skew NumUp NumDn MinLoCord MaxHiCord MaxSubmerge Is_Ogee
51.48,36.7,2.6,0, 10, 10, , , .95, 0, 0,0,,
       0    1346    1393    1488    1527    1531    1600    2600    3600 4600.31
   50.14   50.14   50.15   50.26   50.35   50.56   50.56   50.53   51.31   51.49
                                                                                
       0    1346    1393    1488    1527    1531    1600    2600    3600 4628.98
   50.14   50.14   50.15   50.26   50.35   50.56   50.56   50.53   51.31   51.49
                                                                                
BR Coef=-1 , 0 , 0 ,, 0 ,,,.8,0,,0,
WSPro=,,,, 1 ,,,, 0 ,,,, 0 ,,,,-1 ,-1 ,-1 , 0 , 0 , 0 , 0 , 0
Multiple Barrel Culv=2,4,8,45,.012,.5,1,8,2,44.1,44.5, 2,Culvert #1  , 0 ,47.33
    1488    1488  1496.5  1496.5
Culvert Bottom n=.012
Culvert=1,5,,67,.012,.5,1,1,1,40.27,1526.5,41.44,1526.5,Culvert #2  , 0 ,36.33
Culvert Bottom n=.012
BC Design=,, 0 ,, 0 ,,,,,,

Type RM Length L Ch R = 1 ,5415.974,38.41,38.82,38.69
BEGIN DESCRIPTION:
copy of 443s7u - elevations within channel adjusted based on slope between 443v4 and 443v5 and LIDAR data.  Added surveyed invert elevation d/s of culvert outlets, ~ 14' u/s of this section, as ch. invert for this section.
xsec 2/4
Bank Station offset =      3512
ROB & LOB blocked to close -- watershed divide
LOB adjacent to stream is a canal.  Set n = 0.99 in ROB as flows are ineffective in this area.
END DESCRIPTION:
XS GIS Cut Line= 5
      3212887.51    13903342.841     3212586.087    13904759.624
     3212571.268    13904849.464     3212161.518    13906843.788
     3211984.534    13907882.262
#Sta/Elev= 30
       0   48.29  166.67      47  189.54   48.39  210.23   46.96  492.06   48.19
  728.58   47.27 1116.59   48.17 1170.82   49.58 1232.16   48.36  1247.5   50.23
 1300.67   46.24 1321.84    48.4 1448.49   47.06 1468.05    49.1 1481.27   44.23
    1491   40.37 1502.39   45.23 1545.44   47.51 1599.34   49.17 1903.08   47.49
 2538.33   48.35 2658.07   49.77  2799.9   48.18 2839.72   49.69 2889.04   48.09
 3123.33   49.54 3187.13   48.11 3210.53   49.21 3604.77   48.02 4628.98   50.52
#Mann= 6 ,-1 , 0
       0     .11       0  1247.5     .01       0 1321.84     .11       0
 1468.05     .05       0 1545.44     .11       0 1599.34     .99       0
#XS Ineff= 2 , 0
       0    1465      48    1540       0    48.4
Permanent Ineff=
       F       F
#Block Obstruct= 4 ,-1
  1270.8 1321.84   48.33       0  1247.5      51 4255.68    4700      51
 1444.81    1455   47.67
Bank Sta=1481.27,1502.39
XS Rating Curve= 0
Exp/Cntr=.5,.3

Type RM Length L Ch R = 1 ,5377.154,848.71,837.92,829.49
BEGIN DESCRIPTION:
copy of 443s7u - inverts adjusted based on slope between 443v4 and surveyed d/s culvert invert of xs 2/4 immediately u/s.  xsec 1/4
Bank Station offset =      3526
ROB & LOB blocked to close -- watershed divide
LOB adjacent to stream is a canal
END DESCRIPTION:
XS GIS Cut Line= 5
      3212846.64     13903352.97     3212545.216    13904769.754
     3212530.397    13904859.593     3212086.506    13907020.089
     3211932.456    13907903.093
#Sta/Elev= 30
       0   48.39  131.77   47.29  146.54   48.19  159.91   47.27  510.24   48.28
  722.73   47.28 1124.63   48.36 1160.47    50.1 1203.49   47.48 1237.14   50.52
 1267.71      49 1290.89   46.63 1335.51   48.73  1353.3   49.12 1426.85   45.72
 1437.93   48.36  1453.5   48.97 1466.72    44.1 1473.76   40.22 1487.84    45.1
 1517.11   50.19 1539.55   48.28 1736.01   49.21 1887.91   47.49 2552.71   49.44
 3235.34   48.35 3391.77   49.66 3654.33   48.38 3962.59   49.77 4641.51    49.5
#Mann= 7 ,-1 , 0
       0     .11       0 1267.71     .01       0 1335.51     .11       0
  1453.5     .05       0 1517.11     .11       0 3391.77     .99       0
 3962.59     .11       0
#Block Obstruct= 4 ,-1
    1270 1335.51   48.73    4174    4700   49.87       0 1235.45      52
    1422    1430    46.5
Bank Sta=1466.72,1487.84
XS Rating Curve= 0
Exp/Cntr=.3,.1

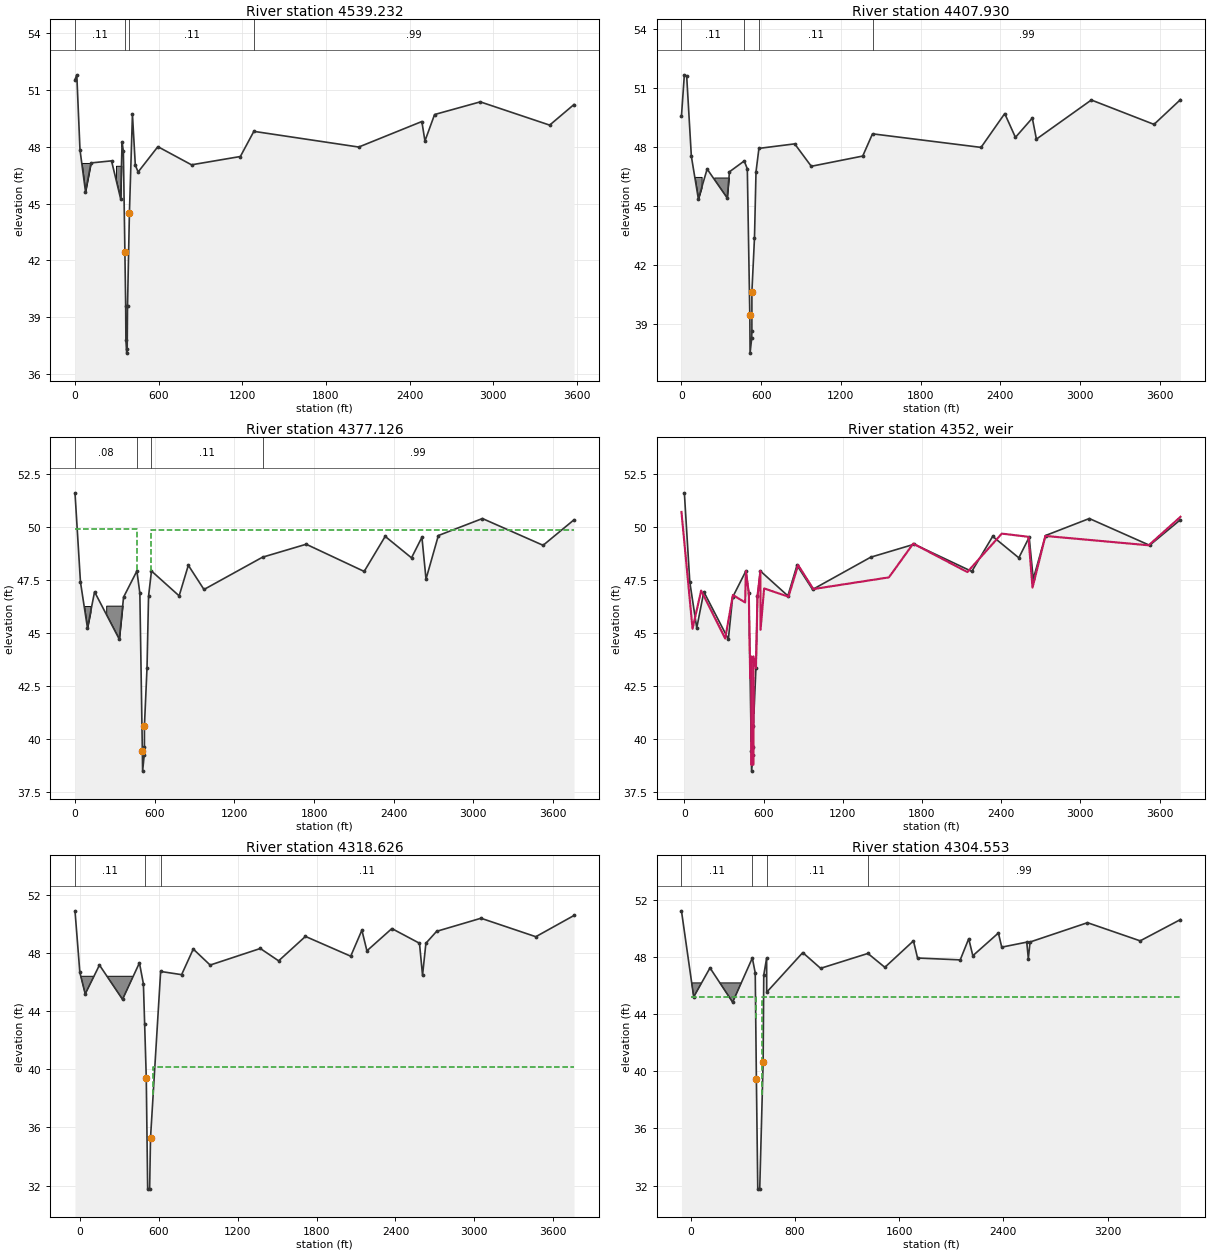
Type RM Length L Ch R = 1 ,4539.232,139.57,131.3,117.2
BEGIN DESCRIPTION:
443v4
Bank Station offset =      4629
Blocked area in LOB not available for flow or storage -- appears to be canal
END DESCRIPTION:
XS GIS Cut Line= 4
       3211630.4    13904392.998     3211700.942    13904722.256
     3211715.952    13904830.876     3211893.813    13907959.014
#Sta/Elev= 30
       0   51.56   12.88   51.81   35.83   47.85   75.37   45.63  114.77   47.15
  262.06   47.26   327.3   45.26  337.86   48.26  346.97   47.76  357.96   42.45
  363.58   39.59  365.16   37.76     371   37.09  374.37   37.29  376.79   39.56
   390.4    44.5  412.07   49.72  432.76   47.03  452.92   46.67  594.52   48.01
   835.9   47.05  1186.3   47.49    1283   48.82 2035.36   47.99 2488.16   49.34
 2510.36   48.31 2579.41   49.71 2907.25   50.38 3404.98   49.15 3579.57   50.24
#Mann= 4 ,-1 , 0
       0     .11       0  357.96    .045       0   390.4     .11       0
    1283     .99       0
#Block Obstruct= 2 ,-1
       0  114.77   47.15  293.91     335      47
Bank Sta=357.96,390.4
XS Rating Curve= 0
Exp/Cntr=.3,.1

Type RM Length L Ch R = 1 ,4407.930,27.02,30.8,26.64
BEGIN DESCRIPTION:
443s6u
xsec 4/4 at Energy Dissipater / Grade Control Structure 443s6B, surveyed.
Bank Station offset =      4483
Blocked area in LOB not available for flow or storage -- appears to be canal
END DESCRIPTION:
XS GIS Cut Line= 6
      3211303.15    13904304.493     3211554.796    13904715.077
     3211599.998    13904800.683     3211633.915    13904934.092
     3211654.747    13905059.083     3211864.988     13907966.22
#Sta/Elev= 30
       0   49.56   21.74   51.66   39.34    51.6   74.52   47.52   127.3   45.35
  193.36   46.87  344.18    45.4  361.51   46.73  472.64   47.28  495.85   46.88
  514.77   39.43  516.73   37.51  528.91   38.27  530.34   38.66  530.43   40.63
  549.91   43.37  561.37   46.73  583.39   47.92  852.56   48.15  977.61   47.01
 1364.96   47.53 1438.53   48.66 2255.83   47.97 2434.17   49.69 2514.83   48.48
 2641.93   49.46 2672.75   48.39 3086.29   50.38 3558.32   49.14 3757.47    50.4
#Mann= 4 ,-1 , 0
       0     .11       0  472.64    .045       0  583.39     .11       0
 1438.53     .99       0
#Block Obstruct= 2 ,-1
       0  151.75   46.47   246.6     370   46.44
Bank Sta=514.77,530.43
XS Rating Curve= 0
Exp/Cntr=.5,.3

Type RM Length L Ch R = 1 ,4377.126,59.48,58.49,58.48
BEGIN DESCRIPTION:
copy of 443s6u -  invert  elevations adjusted based on slope between adjacent surveyed dissipater base elevations and u/s surveyed XS 4/4.
xsec 3/4 at Energy Dissipater / Grade Control Structure 443s6B.  Ineffective elevations based on top of concrete wall elevations at upstream end of dissipater structure.  Ineffective stations based on 1:1 contraction to inside edge of concrete walls of structure.
Bank Station offset =    4491
Blocked area in LOB not available for flow or storage -- appears to be canal
END DESCRIPTION:
XS GIS Cut Line= 6
     3211285.038     13904327.23     3211536.683    13904737.815
     3211581.885    13904823.421     3211615.802    13904956.829
     3211636.634     13905081.82     3211846.875    13907988.958
#Sta/Elev= 30
       0    51.6   41.24    47.4   93.89   45.24  147.41   46.94  333.39   44.71
  365.83   46.69   466.1   47.92  488.34   46.88  507.26   39.43  509.22    38.5
   521.4   39.26  522.83   39.65  522.92   40.63   542.4   43.37  553.86   46.73
  575.88   47.92  784.23   46.75  853.43   48.19  971.25   47.05 1411.96   48.57
    1741   49.18 2177.55    47.9 2335.75   49.55 2533.97   48.54 2612.36   49.51
 2643.18   47.54 2736.14   49.59 3067.99   50.39 3524.94   49.13 3757.47   50.33
#Mann= 4 ,-1 , 0
       0     .08       0   466.1    .025       0  575.88     .11       0
 1411.96     .99       0
#XS Ineff= 2 , 0
       0   466.1   49.89  575.88       0   49.83
Permanent Ineff=
       F       F
#Block Obstruct= 2 ,-1
       0  117.34   46.27  235.06     370   46.29
Bank Sta=507.26,522.92
XS Rating Curve= 0
Exp/Cntr=.5,.3

Type RM Length L Ch R = 5 ,4352    ,,,
BEGIN DESCRIPTION:
Energy Dissipater / Grade Control Structure at 443s6B, RS 4352, modeled as inline weir. Used 2.8 for weir coefficient based on PMT guidance recommendations, structure geometry (flat u/s and d/s slope of ~ 4H:1V), and comparison to weir coefficients for various geometries listed in Tables 5-4 to 5-13 (pp. 5-40 to 5-44) in "Handbook of Hydraulics", 6th Edition (1976), Brater, E.F., and King, H.W.  McGraw-Hill, Inc., New York, N.Y.
END DESCRIPTION:
IW Pilot Flow=0
#Inline Weir SE= 30
     -22    50.7      62    45.2  127.16      47  309.51   44.74  367.58   46.79
  460.45   46.44  466.12   47.92  488.36   46.88  498.97   42.85  506.81    43.9
  506.82    38.8   523.4    38.8  523.41    43.9  542.42   43.37  553.88   46.73
   575.9   47.92   577.3   45.15  604.28    47.1  788.87   46.71  861.75    48.2
  977.19   47.07 1549.72   47.62  1733.9   49.21 2143.78   47.87 2405.18   49.68
 2606.71   49.53 2637.53   47.14 2734.98   49.57 3517.54   49.13 3758.54   50.47
IW Dist,WD,Coef,Skew,MaxSub,Min_El,Is_Ogee,SpillHt,DesHd
10,46,2.8,0,.95,, 0 ,,,2.5,2.5,

Type RM Length L Ch R = 1 ,4318.626,6.42,14.07,18.76
BEGIN DESCRIPTION:
Channel elevations based on nearby surveyed section 443s6u and contour data obtained from TIN.  Inverts adjusted as necessary.
xsec 2/4 at Energy Dissipater / Grade Control Structure 443s6B and xsec 4/4 of 443s6A.  Ineffective elevations based on top of wall elev'ns at d/s end of dissipater.  Ineff. stations based on 1:1 expansion from inside edge of concrete walls of structure.
Bank Station offset =      4483
Blocked canal area in LOB not available for flow or storage.
Cross section extended on LOB
END DESCRIPTION:
XS GIS Cut Line= 6
   3211215.2493313904325.2946764      3211486.23    13904767.425
     3211531.432    13904853.031     3211565.349     13904986.44
     3211586.181    13905111.431     3211796.422    13908018.568
#Sta/Elev= 30
     -37    50.9       0   46.66   40.81   45.18  149.04   47.17  324.51   44.81
  452.95   47.32  483.23   45.88  492.76   43.09  504.98   39.43  515.59   31.76
  530.55   31.76  537.32   35.29  614.31   46.73  773.74   46.51  862.37   48.27
  990.74   47.17 1372.25   48.31 1511.47   47.46 1715.36   49.14 2059.58   47.78
  2144.5   49.57 2182.82   48.15 2372.53   49.68  2582.6   48.67 2605.76   46.46
 2631.32   48.67 2712.86   49.49 3050.27   50.39 3467.09   49.12 3757.47   50.58
#Mann= 3 ,-1 , 0
     -37     .11       0  492.76    .045       0  614.31     .11       0
#XS Ineff= 2 , 0
       0     497    40.1     557       0   40.13
Permanent Ineff=
       F       F
#Block Obstruct= 2 , 0
       0     400    46.4               0
Bank Sta=504.98,537.32
XS Rating Curve= 0
Exp/Cntr=.5,.3

Type RM Length L Ch R = 1 ,4304.553,128.74,120.62,120.62
BEGIN DESCRIPTION:
Channel elevations based on nearby surveyed section 443s6u and contour data obtained from TIN.  Invert  elevations adjusted as necessary
xsec 1/4 at Energy Dissipater / Grade Control Structure 443s6B and xsec 3/4 of 443s6A
Bank Station offset =      4483
Cross section extended on LOB
blocked area in LOB not available for flow or storage -- appears to be canal
END DESCRIPTION:
XS GIS Cut Line= 6
  3211180.61187413904308.0624198     3211482.125    13904772.449
      3211510.34    13904865.557     3211549.495    13904996.372
     3211570.327    13905121.363     3211780.568    13908028.501
#Sta/Elev= 30
     -70   51.22   23.88    45.2  149.03   47.23  322.67   44.83  473.82   47.92
  496.06   46.88  504.98   39.43  515.59   31.76  530.55   31.76  556.64   40.63
  561.58   46.73   583.6   47.92  584.12   45.53  860.81    48.3  997.77    47.2
 1360.63   48.24 1490.65   47.27 1710.18   49.12 1741.61   47.92    2069   47.79
 2134.27   49.27 2165.74   48.08 2361.98   49.67 2387.58   48.68 2579.55   49.03
 2591.62   47.88 2604.95   49.04 3045.58   50.39 3449.75   49.12 3758.97   50.61
#Mann= 4 ,-1 , 0
     -70     .11       0  473.82    .045       0   583.6     .11       0
 1360.63     .99       0
#XS Ineff= 2 , 0
       0     500   45.22     550       0   45.22
Permanent Ineff=
       F       F
#Block Obstruct= 2 , 0
       0     400   46.18               0
Bank Sta=504.98,556.64
XS Rating Curve= 0
Exp/Cntr=.5,.3

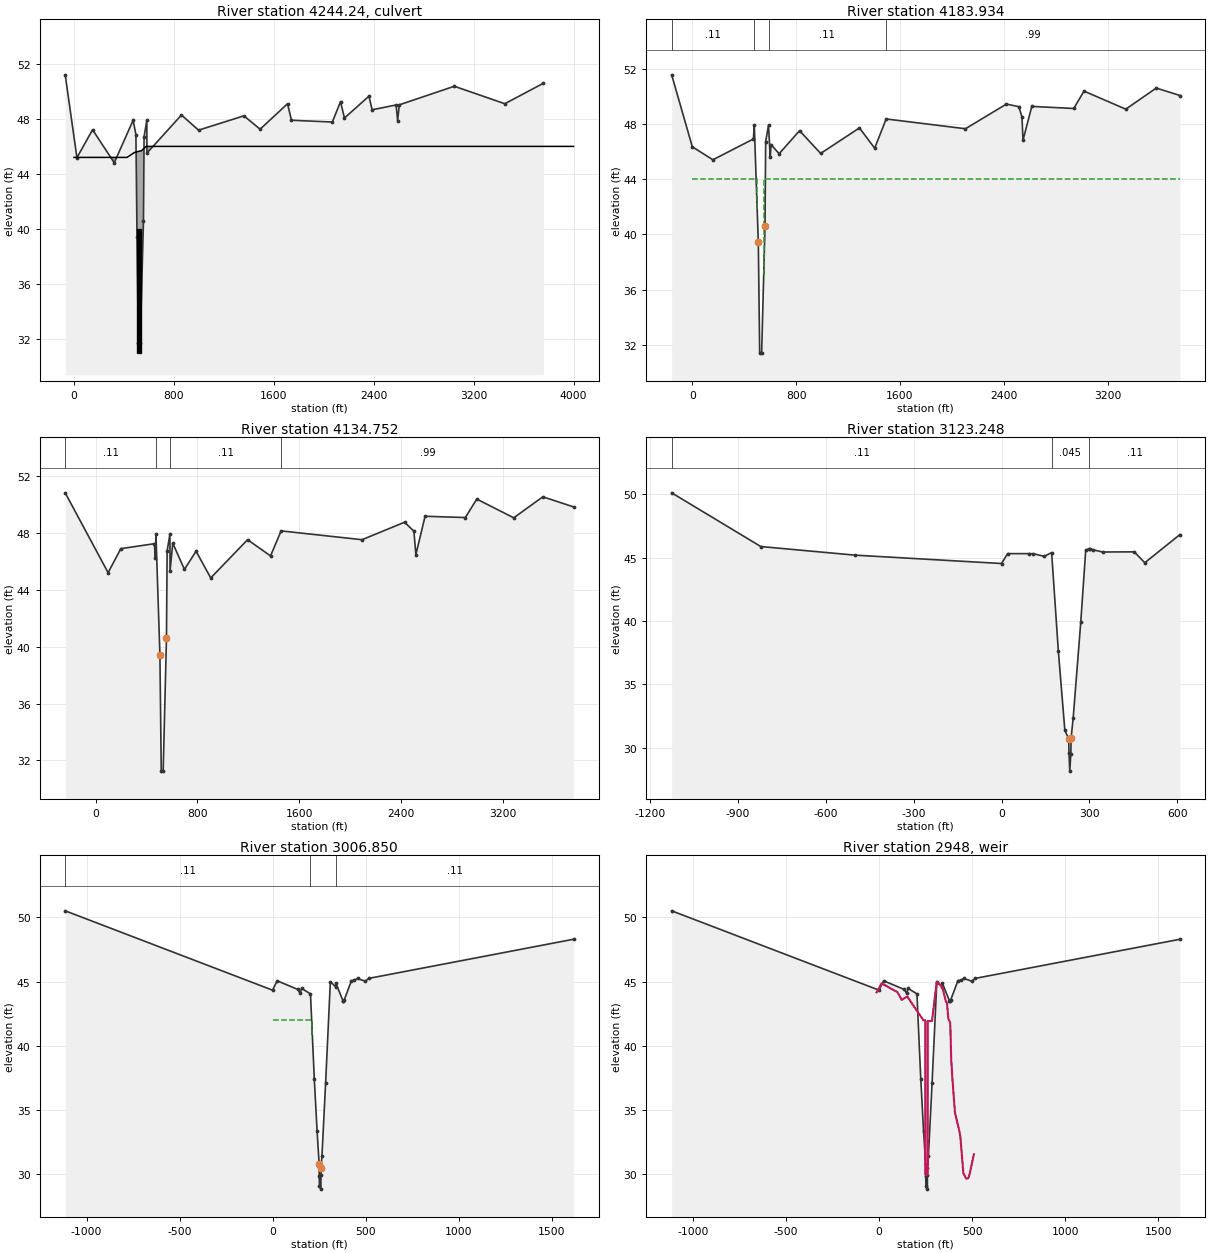
Type RM Length L Ch R = 2 ,4244.24 ,,,
BEGIN DESCRIPTION:
443s6a; Marlin Spikeway
END DESCRIPTION:
Bridge Culvert--1,0,-1,-1, 0
Deck Dist Width WeirC Skew NumUp NumDn MinLoCord MaxHiCord MaxSubmerge Is_Ogee
46.16,28.13,2.6,0, 7, 7, , , .95, 0, 0,0,,
       0     425     483     517     540     578    4000
   45.22   45.22   45.57   45.66    45.7   46.02   46.02
                                                        
       0     428     486     520     543     581    4000
   45.22   45.22   45.57   45.66    45.7   46.02   46.02
                                                        
BR Coef=-1 , 0 , 0 ,, 0 ,,,.8,0,,0,
WSPro=,,,, 1 ,,,, 0 ,,,, 0 ,,,,-1 ,-1 ,-1 , 0 , 0 , 0 , 0 , 0
Multiple Barrel Culv=2,9,9,80.5,.012,.5,1,8,2,31,30.99, 3,Culvert #1  , 0 ,20.06
     512     515     522     525     532     535
Culvert Bottom n=.012
BC Design=,, 0 ,, 0 ,,,,,,

Type RM Length L Ch R = 1 ,4183.934,49.11,49.18,49.78
BEGIN DESCRIPTION:
Channel elevations based on nearby surveyed section 443s6u and contour data obtained from TIN. Invert  elevations adjusted as necessary
xsec 2/4 of 443s6A.
Bank Station offset =      4480
Cross section extended on LOB
END DESCRIPTION:
XS GIS Cut Line= 6
 3211031.908561913904282.0458314      3211366.64    13904828.195
     3211411.843    13904913.801      3211445.76    13905047.209
     3211466.592      13905172.2     3211676.832    13908079.338
#Sta/Elev= 30
    -159   51.57       0   46.35  158.89   45.41  470.75   46.92  477.37   47.92
  508.53   39.43  519.14   31.39   534.1   31.39  560.19   40.63  565.13   46.73
  587.15   47.92   600.5   45.59  606.54   46.51  669.02   45.85  826.35   47.52
   988.8   45.87  1287.7   47.72 1405.04   46.25 1493.47   48.37 2104.49   47.66
 2420.18   49.45  2515.7   49.26 2539.92   48.51 2548.01   46.84 2615.79   49.28
 2939.03   49.13 3017.56   50.39 3339.76   49.08 3574.39   50.61 3757.47   50.07
#Mann= 4 ,-1 , 0
    -159     .11       0  477.37    .045       0  587.15     .11       0
 1493.47     .99       0
#XS Ineff= 2 , 0
       0     500      44     550       0      44
Permanent Ineff=
       F       F
Bank Sta=508.53,560.19
XS Rating Curve= 0
Exp/Cntr=.5,.3

Type RM Length L Ch R = 1 ,4134.752,1002.15,1011.5,1004.53
BEGIN DESCRIPTION:
Invert  elevations adjusted as necessary.  Channel elevations based on nearby surveyed section 443s6u and contour data obtained from TIN.
xsec 1/4 of 443s6A
Bank Station offset =      4483
Cross section extended on LOB
END DESCRIPTION:
XS GIS Cut Line= 6
 3210950.382508513904243.2238399     3211327.441    13904858.434
     3211372.644     13904944.04     3211406.561    13905077.448
     3211427.392     13905202.44     3211637.633    13908109.577
#Sta/Elev= 30
    -240   50.83   97.27   45.21  197.39    46.9   461.2   47.25  469.36   46.21
  473.61   47.92  504.77   39.43  515.38   31.24  530.34   31.24  556.43   40.63
  561.37   46.73  583.39   47.92  584.73   45.36  605.81   47.29  697.39   45.44
  789.13   46.72  904.42   44.84 1193.96   47.53 1374.72   46.39 1457.92   48.15
  2094.2   47.53 2428.56   48.76 2502.19   48.13  2517.7   46.48 2590.04   49.18
  2906.6   49.09 2996.66   50.39 3287.28   49.07 3516.09   50.55 3757.47   49.84
#Mann= 4 ,-1 , 0
    -240     .11       0  473.61    .045       0  583.39     .11       0
 1457.92     .99       0
Bank Sta=504.77,556.43
XS Rating Curve= 0
Exp/Cntr=.3,.1

Type RM Length L Ch R = 1 ,3123.248,105.83,116.4,127.9
BEGIN DESCRIPTION:
xsec 4/4 at Energy Dissipater / Grade Control Structure 443s5, surveyed.
Bank Station offset =      4767
END DESCRIPTION:
XS GIS Cut Line= 6
      3210661.0813904194.8279239     3210484.139    13905296.335
      3210503.45    13905403.164     3210525.199    13905439.151
     3210597.057    13905564.567 3210761.252242613905831.8221999
#Sta/Elev= 26
   -1125   50.13    -821   45.89    -500   45.21       0   44.55   20.92   45.33
   92.46   45.33  108.56   45.32  145.77   45.12     171   45.41  193.91   37.62
  216.03   31.39  229.21    30.7  230.17    29.6  232.87   28.16  236.43    29.5
   237.3   30.76   244.4   32.33  270.37   39.93  287.29   45.61  299.18   45.72
  301.11    45.7  312.78   45.63  344.68   45.46  452.88   45.47  488.72   44.61
  608.82   46.84
#Mann= 3 ,-1 , 0
   -1125     .11       0     171    .045       0  299.18     .11       0
Bank Sta=229.21,237.3
XS Rating Curve= 0
Exp/Cntr=.5,.3

Type RM Length L Ch R = 1 ,3006.850,68.1,114.18,147.23
BEGIN DESCRIPTION:
443s5u
xsec 3/4 at Energy Dissipater / Grade Control Structure 443s5, surveyed.  Ineffective elevations based on top of concrete wall elevations at upstream end of dissipater structure.  Ineffective stations based on 1:1 contraction to inside edge of concrete walls of structure.
Bank Station offset =      4740
END DESCRIPTION:
XS GIS Cut Line= 6
      3210661.0813904194.8279239     3210476.711    13905294.478
     3210450.711    13905449.546     3210463.731    13905632.262
     3210485.748    13905808.726 3210621.906783713906900.0247055
#Sta/Elev= 29
   -1115    50.5       0   44.33   24.47   45.06  135.15   44.39  148.55   44.08
  155.98   44.47  203.72   44.04  224.31   37.41  239.28   33.37  250.31   30.82
  250.66   29.85  252.12    29.1  259.74   28.86  259.94   29.92  260.42   30.54
  265.37   31.43  284.96   37.08  310.54   44.99  340.45   44.57  340.88   44.85
  378.32   43.51  379.94   43.45  384.97   43.56  423.68   45.06  440.36   45.12
  456.59   45.24   498.1   45.03  518.24   45.25    1618   48.29
#Mann= 3 ,-1 , 0
   -1115     .11       0  203.72     .02       0  340.88     .11       0
#XS Ineff= 2 , 0
       0     214   41.98     304       0   41.93
Permanent Ineff=
       F       F
Bank Sta=250.31,260.42
XS Rating Curve= 0
Exp/Cntr=.5,.3

Type RM Length L Ch R = 5 ,2948    ,,,
BEGIN DESCRIPTION:
Energy dissipater / Grade control structure 443s5, at RS 2948, modeled as inline weir. Used 2.65 for weir coefficient based on PMT guidance recommendations, structure geometry (flat u/s and d/s slope of ~ 4H:1V), and comparison to weir coefficients for various geometries listed in Tables 5-4 to 5-13 (pp. 5-40 to 5-44) in "Handbook of Hydraulics", 6th Edition (1976), Brater, E.F., and King, H.W.  McGraw-Hill, Inc., New York, N.Y. also to remove non-converging message at inline weir within HEC-RAS warnings.
END DESCRIPTION:
IW Pilot Flow=0
#Inline Weir SE= 27
     -13   44.16   13.98   44.86   99.37   44.17   121.2   43.58  151.79   43.83
   238.9   41.98  248.49   41.98  248.49   29.99  261.48   29.99  261.49   41.93
  284.58   41.93  310.16   44.99  340.07   44.57   360.3    43.4  365.32   43.33
  372.33   42.12  382.69   41.81  387.91   38.97  394.28   37.46  408.22    34.8
  430.08   33.49  436.93   32.95  453.22   30.12   467.9   29.68  479.55    29.7
  487.07   30.04  509.72   31.57
IW Dist,WD,Coef,Skew,MaxSub,Min_El,Is_Ogee,SpillHt,DesHd
38,44,2.65,0,.95,, 0 ,,,2.5,2.5,

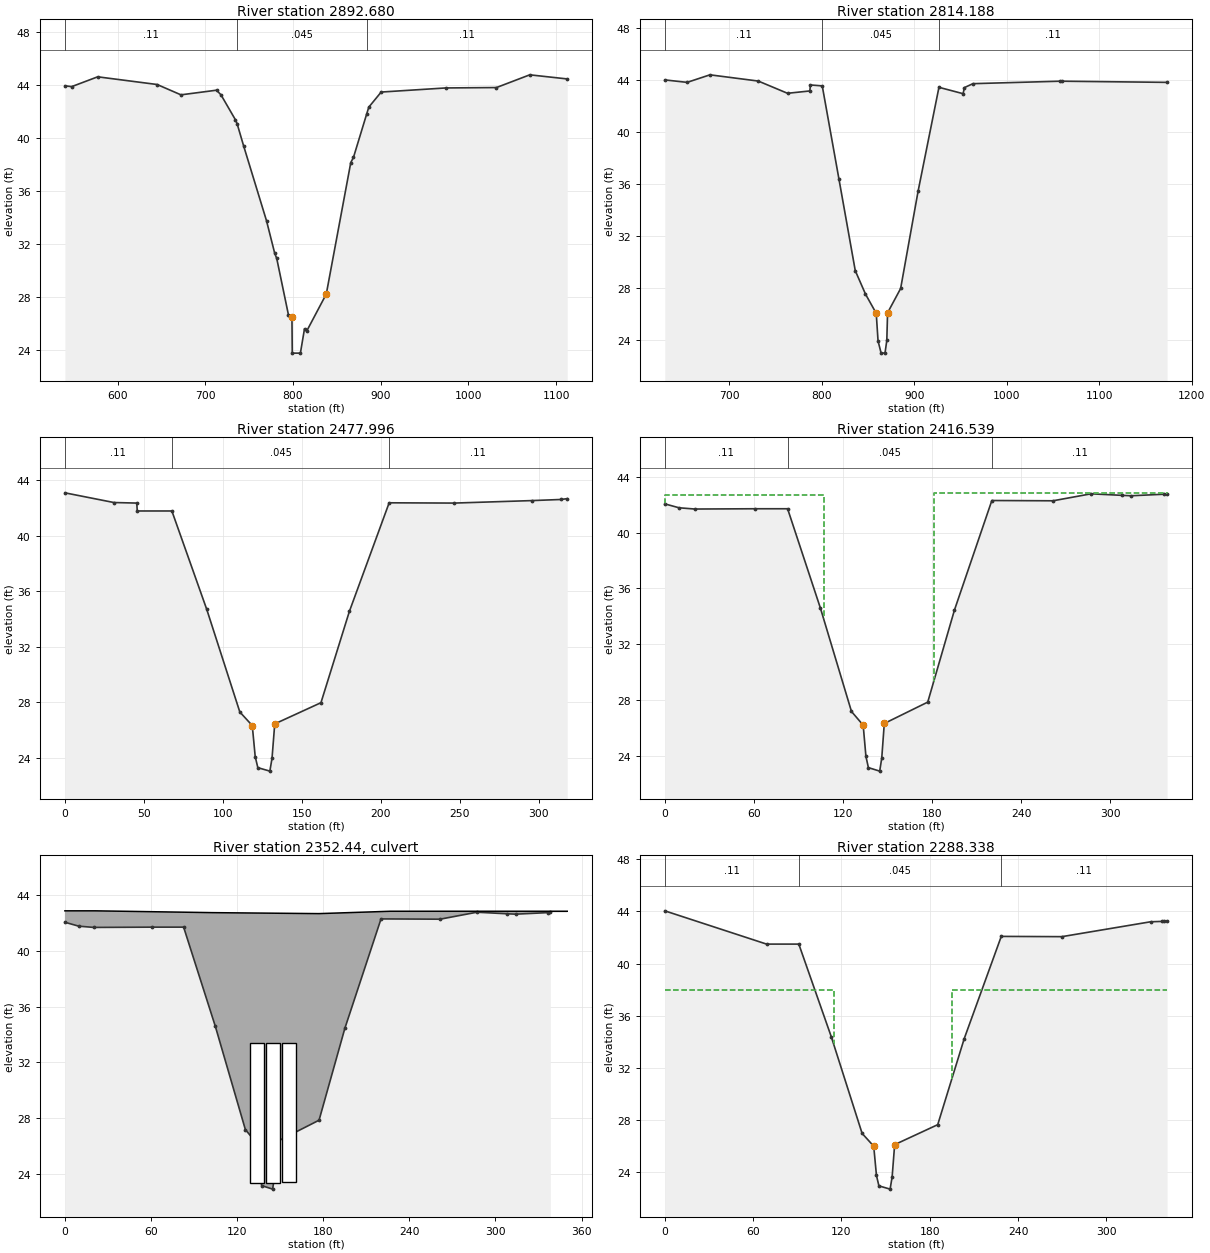
Type RM Length L Ch R = 1 ,2892.680,69.01,78.49,79.2
BEGIN DESCRIPTION:
copy of 443s5u
xsec 2/4 at Energy Dissipater / Grade Control Structure 443s5.  Ineffective elevations based on top of concrete wall elevations at downstream end of dissipater structure.  Ineffective stations based on 1:1 expansion from inside edge of concrete walls of structure.
Bank Station offset =      4732
END DESCRIPTION:
XS GIS Cut Line= 6
 3210551.818776713904723.6586956     3210397.602    13905470.077
     3210379.167    13905500.363     3210352.163    13905524.037
     3210279.205     13905552.12 3209564.029389813905834.0099392
#Sta/Elev= 29
     540   43.94  547.75   43.88  577.39   44.62  645.11   44.04   672.3   43.26
  712.83   43.61  717.93   43.26  734.38   41.38  736.33   41.08  743.69   39.42
  769.83   33.76   779.2    31.3  781.47   30.92  794.77   26.68  798.84   26.46
  799.19   23.77  808.47   23.77  813.15   25.61   815.7   25.44  837.99   28.23
   865.9   38.15  868.97   38.54  883.92   41.79  886.43   42.33  900.55   43.47
  974.15   43.78 1031.98   43.81 1069.95   44.77 1112.65   44.46
#Mann= 3 ,-1 , 0
     540     .11       0  736.33    .045       0  883.92     .11       0
#XS Ineff= 2 , 0
       0     762   34.65     875       0   34.15
Permanent Ineff=
       F       F
Bank Sta=798.84,837.99
XS Rating Curve= 0
Exp/Cntr=.5,.3

Type RM Length L Ch R = 1 ,2814.188,349.05,336.19,321.19
BEGIN DESCRIPTION:
443v2
xsec 1/4 at Energy Dissipater / Grade Control Structure 443s5.
Bank Station offset =      4766
END DESCRIPTION:
XS GIS Cut Line= 6
  3210528.63192613904810.7479737     3210396.855    13905423.547
     3210387.123    13905426.164      3210249.37    13905479.189
 3209496.979504913905775.7459732 3209450.462474513905794.0808004
#Sta/Elev= 26
     630   44.01  654.22   43.82  678.88    44.4  731.19   43.92  762.79   42.98
  786.92   43.16  787.57   43.62  800.35   43.55  818.45   36.37  836.07   29.34
  847.12   27.54  858.74   26.06  860.72   23.93  864.04      23  868.25   23.01
  870.19   23.98  871.01    26.1  885.14   27.97  903.99   35.44  926.58   43.44
  952.67   42.95  954.17   43.42  963.33   43.72 1057.58   43.91 1059.23   43.91
 1173.33   43.82
#Mann= 3 ,-1 , 0
     630     .11       0  800.35    .045       0  926.58     .11       0
Bank Sta=858.74,871.01
XS Rating Curve= 0
Exp/Cntr=.3,.1

Type RM Length L Ch R = 1 ,2477.996,61.14,61.46,61
BEGIN DESCRIPTION:
443s4u
xsec 4/4 at Port O call
Bank Station offset =      4870
END DESCRIPTION:
XS GIS Cut Line= 2
     3210215.203    13905109.523     3209986.323    13905330.228
#Sta/Elev= 20
       0   43.11   31.02   42.41   45.48   42.37    45.8    41.8   67.71    41.8
    89.8   34.69  110.72   27.29   118.6   26.31  120.46   24.07  122.12   23.27
  129.73   23.02  131.11   23.95  132.82   26.43  162.08   27.96  180.07   34.55
  205.25   42.39  246.43   42.37   295.7   42.55  314.07   42.63  317.96   42.69
#Mann= 3 ,-1 , 0
       0     .11       0   67.71    .045       0  205.25     .11       0
Bank Sta=118.6,132.82
XS Rating Curve= 0
Exp/Cntr=.5,.3

Type RM Length L Ch R = 1 ,2416.539,133.89,128.2,128.2
BEGIN DESCRIPTION:
copy of 443s4u
inverts adjusted based on slope between 443s3u and 443v2
xsec 3/4 at Port O call
Bank Station offset =      4855
END DESCRIPTION:
XS GIS Cut Line= 2
     3210174.332    13905068.652     3209929.103    13905301.618
#Sta/Elev= 22
       0   42.05    9.62   41.77   20.19   41.68   60.81    41.7   82.72    41.7
  104.81   34.59  125.73   27.19  133.61   26.21  135.47   23.97  137.13   23.17
  144.74   22.92  146.12   23.85  147.83   26.33  177.09   27.86  195.08   34.45
  220.26   42.29  261.44   42.27  287.08   42.77   307.8   42.66  314.07   42.63
  336.28   42.74  338.25   42.77
#Mann= 3 ,-1 , 0
       0     .11       0   82.72    .045       0  220.26     .11       0
#XS Ineff= 2 , 0
       0     107   42.67     181       0   42.84
Permanent Ineff=
       F       F
Bank Sta=133.61,147.83
XS Rating Curve= 0
Exp/Cntr=.5,.3

Type RM Length L Ch R = 2 ,2352.44 ,,,
BEGIN DESCRIPTION:
443s4; Port O call
END DESCRIPTION:
Bridge Culvert--1,0,-1,-1, 0
Deck Dist Width WeirC Skew NumUp NumDn MinLoCord MaxHiCord MaxSubmerge Is_Ogee
49.35,29.5,2.6,0, 7, 7, , , .95, 0, 0,0,,
       0      21     103     177     227     295     350
   42.87   42.87   42.74   42.67   42.84   42.84   42.84
                                                        
       0      29     111     185     235     303     350
   42.87   42.87   42.74   42.67   42.84   42.84   42.84
                                                        
Culvert=2,10,10,90,.012,.5,1,8,2,23.38,134,23.14,142,Culvert #1  , 0 ,19.1
Culvert Bottom n=.012
Culvert=2,10,10,90,.012,.5,1,8,2,23.38,145,23.22,153,Culvert #2  , 0 ,19.1
Culvert Bottom n=.012
Culvert=2,10,10,90,.012,.5,1,8,2,23.41,156,23.2,164,Culvert #3  , 0 ,19.1
Culvert Bottom n=.012
BC Design=,, 0 ,, 0 ,,,,,,

Type RM Length L Ch R = 1 ,2288.338,56.03,57.56,48.62
BEGIN DESCRIPTION:
copy of 443s4u
inverts adjusted based on slope between 443s3u and 443v2
xsec 2/4 at Port O call
Bank Station offset =      4847
END DESCRIPTION:
XS GIS Cut Line= 5
     3210072.153    13905003.257     3209961.572    13905100.994
     3209940.044    13905122.204     3209924.061    13905141.414
     3209847.361     13905256.66
#Sta/Elev= 19
       0   44.05   69.15    41.5   91.06    41.5  113.15   34.39  134.07   26.99
  141.95   26.01  143.81   23.77  145.47   22.97  153.08   22.72  154.46   23.65
  156.17   26.13  185.43   27.66  203.42   34.25   228.6   42.09  269.78   42.07
  330.03   43.21  337.82   43.24  339.37   43.26  341.23   43.27
#Mann= 3 ,-1 , 0
       0     .11       0   91.06    .045       0   228.6     .11       0
#XS Ineff= 2 , 0
       0     115   37.95     195       0   37.95
Permanent Ineff=
       F       F
Bank Sta=141.95,156.17
XS Rating Curve= 0
Exp/Cntr=.5,.3