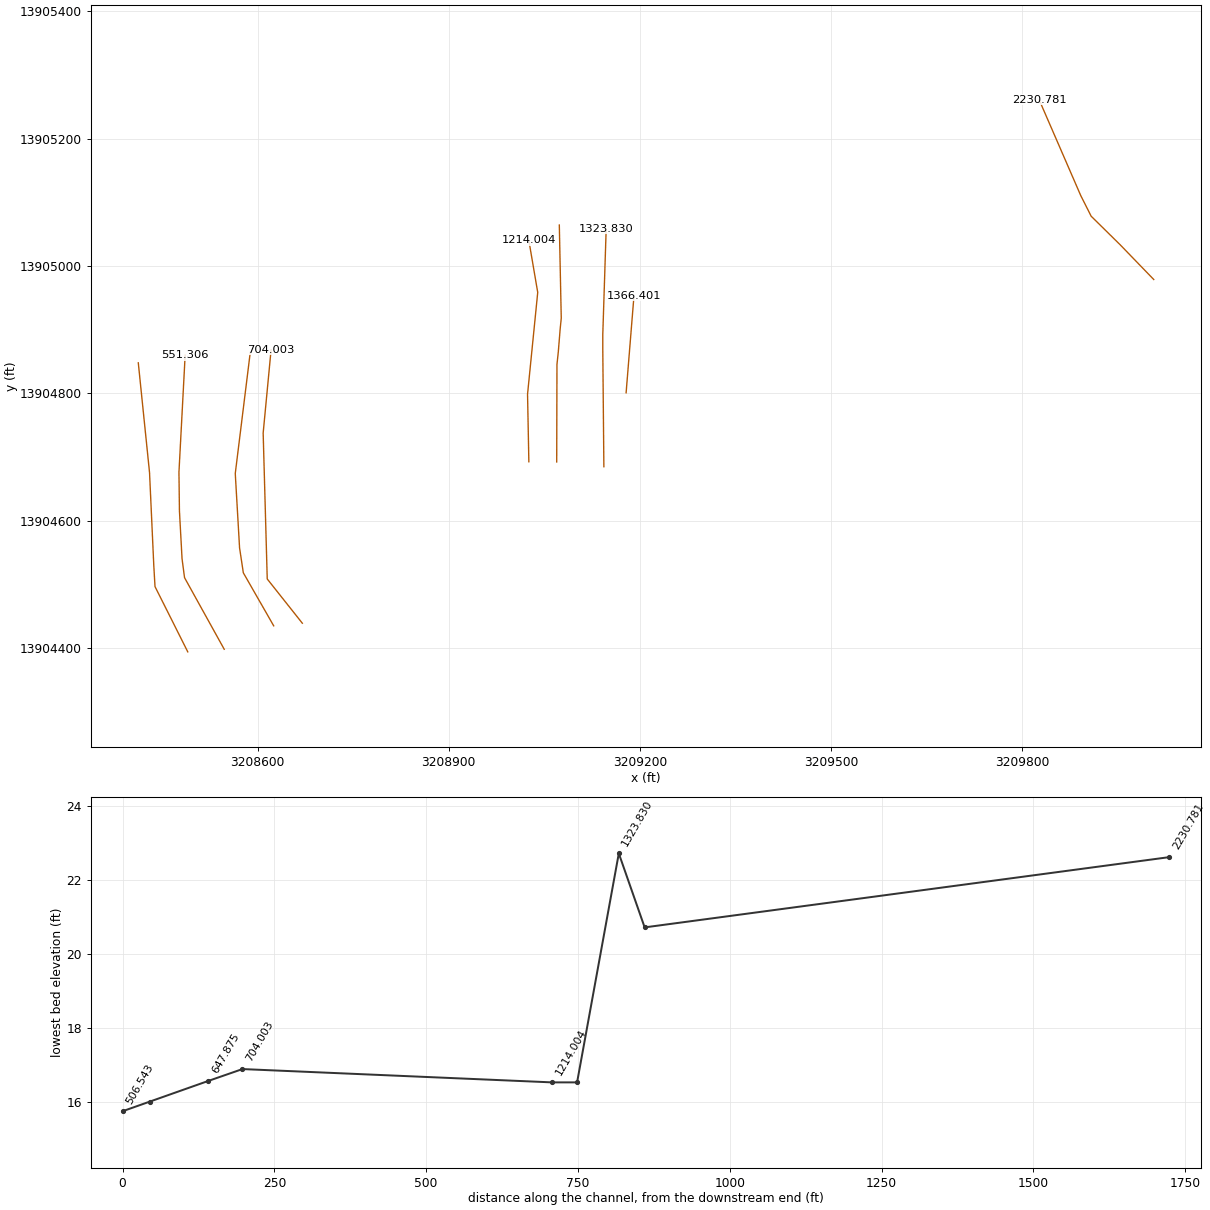
HEC-RAS study R102-03-00.prj: R102-03-00

--- R102-03-00.g03 (geometry) --- (continued)

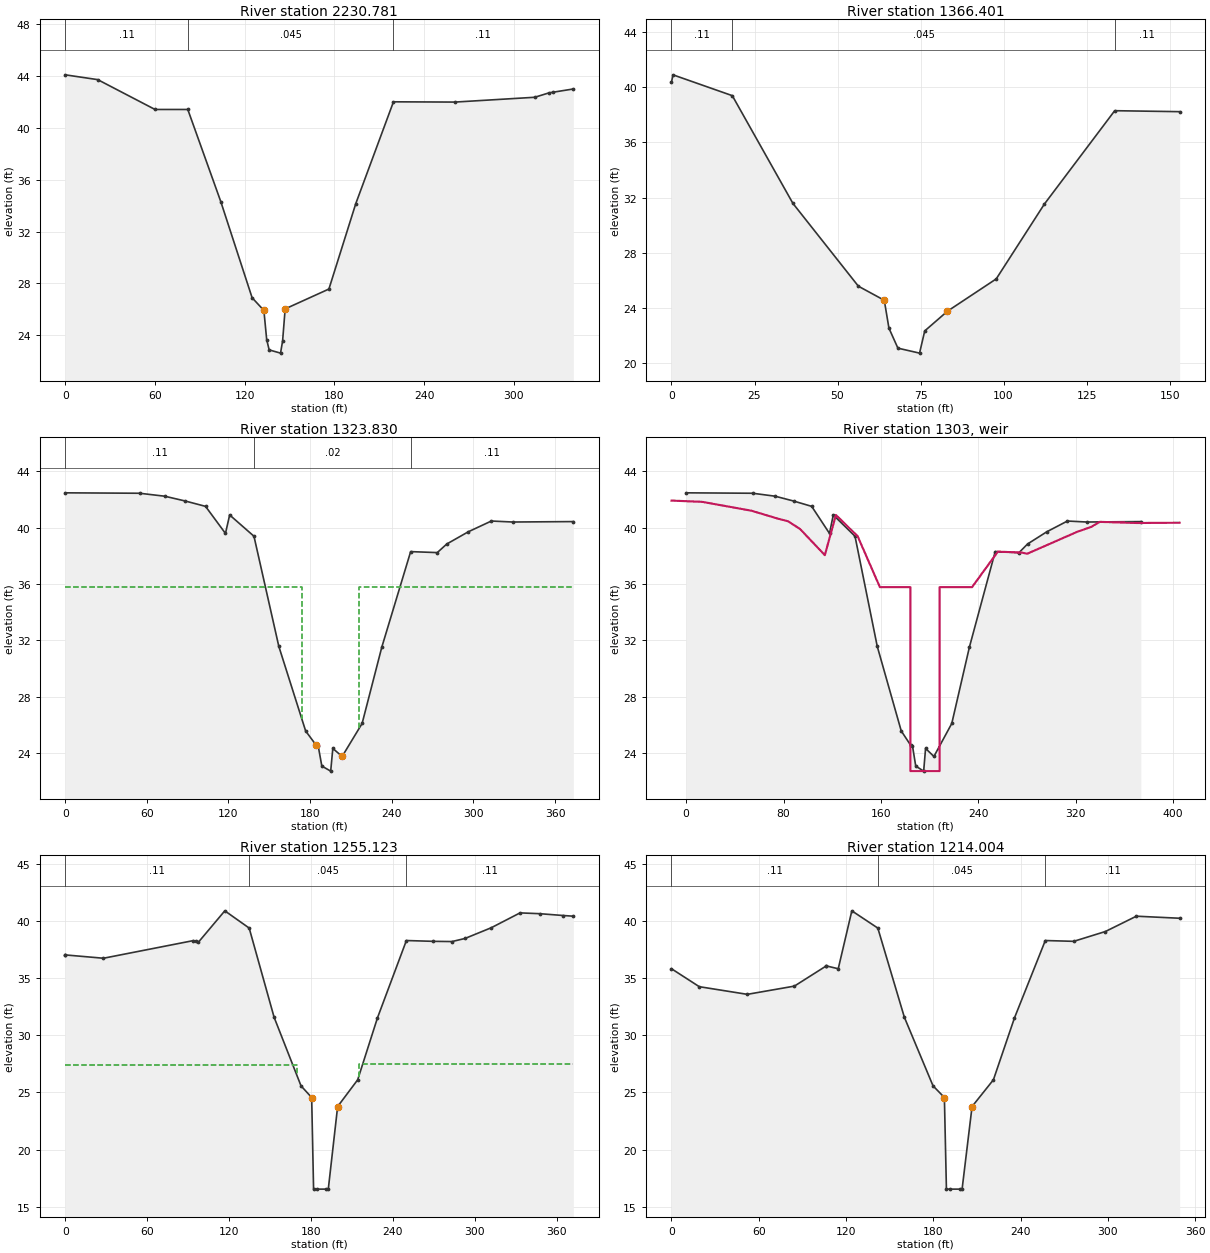
Type RM Length L Ch R = 1 ,2230.781,847.33,864.38,843.46
BEGIN DESCRIPTION:
copy of 443s4u
inverts adjusted based on slope between 443s3u and 443v2
xsec 1/4 at Port O call
Bank Station offset =      4856
END DESCRIPTION:
XS GIS Cut Line= 5
     3210006.759    13904978.734     3209954.106    13905033.198
     3209908.523    13905078.107     3209892.219     13905110.41
     3209826.925    13905260.747
#Sta/Elev= 20
       0   44.08   21.74   43.71   60.07   41.41   81.98   41.41  104.07    34.3
  124.99    26.9  132.87   25.92  134.73   23.68  136.39   22.88     144   22.63
  145.38   23.56  147.09   26.04  176.35   27.57  194.34   34.16  219.52      42
   260.7   41.98     314   42.35  323.54   42.69  326.24   42.74  339.83   42.99
#Mann= 3 ,-1 , 0
       0     .11       0   81.98    .045       0  219.52     .11       0
Bank Sta=132.87,147.09
XS Rating Curve= 0
Exp/Cntr=.3,.1

Type RM Length L Ch R = 1 ,1366.401,40.74,42.57,46.21
BEGIN DESCRIPTION:
443s3u
xsec 4/4 at Energy Dissipater / Grade Control Structure 443s3, surveyed.
Bank Station offset =      4925
END DESCRIPTION:
XS GIS Cut Line= 2
     3209178.507    13904800.915     3209190.842    13904952.997
#Sta/Elev= 15
       0   40.37     .45    40.9   18.31   39.39   36.57   31.58   56.28   25.58
   64.08   24.56   65.48   22.54   68.18   21.09    74.7   20.73   76.26   22.34
   83.11   23.77   97.79   26.11  112.28   31.53  133.47    38.3  153.03   38.23
#Mann= 3 ,-1 , 0
       0     .11       0   18.31    .045       0  133.47     .11       0
Bank Sta=64.08,83.11
XS Rating Curve= 0
Exp/Cntr=.5,.3

Type RM Length L Ch R = 1 ,1323.830,71.04,68.71,68.71
BEGIN DESCRIPTION:
copy of 443s3u - elevations adjusted based on slope between XS 4/4 and adjacent dissipater base elevations.
xsec 3/4 at Energy Dissipater / Grade Control Structure 443s3.  Ineffective elevations based on top of concrete wall elevations at upstream end of dissipater structure.  Ineffective stations based on 1:1 contraction to inside edge of concrete walls of structure.
Bank Station offset =    4805
END DESCRIPTION:
XS GIS Cut Line= 4
     3209143.602    13904684.897     3209141.893    13904869.775
     3209141.893    13904892.202     3209147.227    13905058.278
#Sta/Elev= 25
       0   42.47   54.67   42.44   73.14   42.23   88.22   41.89  103.14   41.51
  117.78   39.59  120.87    40.9  138.73   39.39  156.99   31.58   176.7   25.58
   184.5   24.56   185.9   24.54   188.6   23.09  195.12   22.73  196.68   24.34
  203.53   23.77  218.21   26.11   232.7   31.53  253.89    38.3  273.45   38.23
  280.44   38.84  296.31   39.71   313.2   40.47  328.89    40.4  373.47   40.43
#Mann= 3 ,-1 , 0
       0     .11       0  138.73     .02       0  253.89     .11       0
#XS Ineff= 2 , 0
       0     174   35.78     216       0   35.78
Permanent Ineff=
       F       F
Bank Sta=184.5,203.53
XS Rating Curve= 0
Exp/Cntr=.5,.3

Type RM Length L Ch R = 5 ,1303    ,,,
BEGIN DESCRIPTION:
Energy Dissipater / Grade Control Structure at 443s3.  RS 1303, modeled as inline weir. Used 3 for weir coefficient based on PMT guidance recommendations, structure geometry (flat u/s and d/s slope of ~ 4H:1V), and comparison to weir coefficients for various geometries listed in Tables 5-4 to 5-13 (pp. 5-40 to 5-44) in "Handbook of Hydraulics", 6th Edition (1976), Brater, E.F., and King, H.W.  McGraw-Hill, Inc., New York, N.Y., also to remove non-converging message at inline weir within HEC-RAS warnings.
END DESCRIPTION:
IW Pilot Flow=0
#Inline Weir SE= 25
     -12   41.92   13.23   41.83   53.69    41.2   75.69   40.63   83.82   40.45
   93.64    39.9  113.95   38.05  123.04    40.9   140.9   39.39  159.16   35.78
  178.87   35.78  184.19   35.78  184.19   22.73  208.18   22.73  208.19   35.78
  220.38   35.78  234.87   35.78  256.06    38.3  275.62   38.23  280.17   38.15
  321.36   39.71  332.59   40.05  339.82   40.41  370.52   40.33  405.38   40.35
IW Dist,WD,Coef,Skew,MaxSub,Min_El,Is_Ogee,SpillHt,DesHd
7,48,3,0,.95,, 0 ,,,2.5,2.5,

Type RM Length L Ch R = 1 ,1255.123,41.12,41.12,41.71
BEGIN DESCRIPTION:
copy of 443s3u - elevations adjusted as necessary
xsec 2/4 at Energy Dissipater / Grade Control Structure 443s3. Ineffective elevations based on top of concrete wall elevations at downstream end of dissipater structure.  Ineffective stations based on 1:1 expansion from inside edge of concrete walls of structure.
Bank Station offset =    4809
END DESCRIPTION:
XS GIS Cut Line= 6
     3209069.573    13904692.357     3209069.974    13904845.434
     3209072.104    13904865.446     3209074.978     13904900.88
     3209076.713    13904917.974      3209073.66    13905064.287
#Sta/Elev= 27
       0   37.05     .11   37.04   28.04   36.75   93.73   38.29   95.67   38.26
   97.63   38.16  116.93    40.9  134.79   39.39  153.05   31.58  172.76   25.58
  180.56   24.56  181.96   16.54  184.66   16.54  191.18   16.54  192.74   16.54
  199.59   23.77  214.27   26.11  228.76   31.53  249.95    38.3  269.51   38.23
  283.36   38.21  292.87   38.48  312.14   39.42  333.22   40.72  347.61   40.65
  364.83   40.49  372.28   40.43
#Mann= 3 ,-1 , 0
       0     .11       0  134.79    .045       0  249.95     .11       0
#XS Ineff= 2 , 0
       0     170   27.39     215       0    27.5
Permanent Ineff=
       F       F
Bank Sta=180.56,199.59
XS Rating Curve= 0
Exp/Cntr=.5,.3

Type RM Length L Ch R = 1 ,1214.004,511.79,510,498.67
BEGIN DESCRIPTION:
copy of 443s3u - elevations adjusted as necessary
xsec 1/4 at Energy Dissipater / Grade Control Structure 443s3.
Bank Station offset =      4802
END DESCRIPTION:
XS GIS Cut Line= 4
     3209025.846    13904692.635     3209023.797    13904798.681
     3209039.771    13904958.541     3209025.846    13905040.042
#Sta/Elev= 24
       0   35.83    19.1   34.26   52.13   33.59    84.5   34.31  106.07   36.05
  106.43   36.08  114.65   35.83     124    40.9  141.86   39.39  160.12   31.58
  179.83   25.58  187.63   24.56  189.03   16.54  191.73   16.54  198.25   16.54
  199.81   16.54  206.66   23.77  221.34   26.11  235.83   31.53  257.02    38.3
  276.58   38.23  298.35   39.09  319.63   40.43   349.4   40.25
#Mann= 3 ,-1 , 0
       0     .11       0  141.86    .045       0  257.02     .11       0
Bank Sta=187.63,206.66
XS Rating Curve= 0
Exp/Cntr=.3,.1

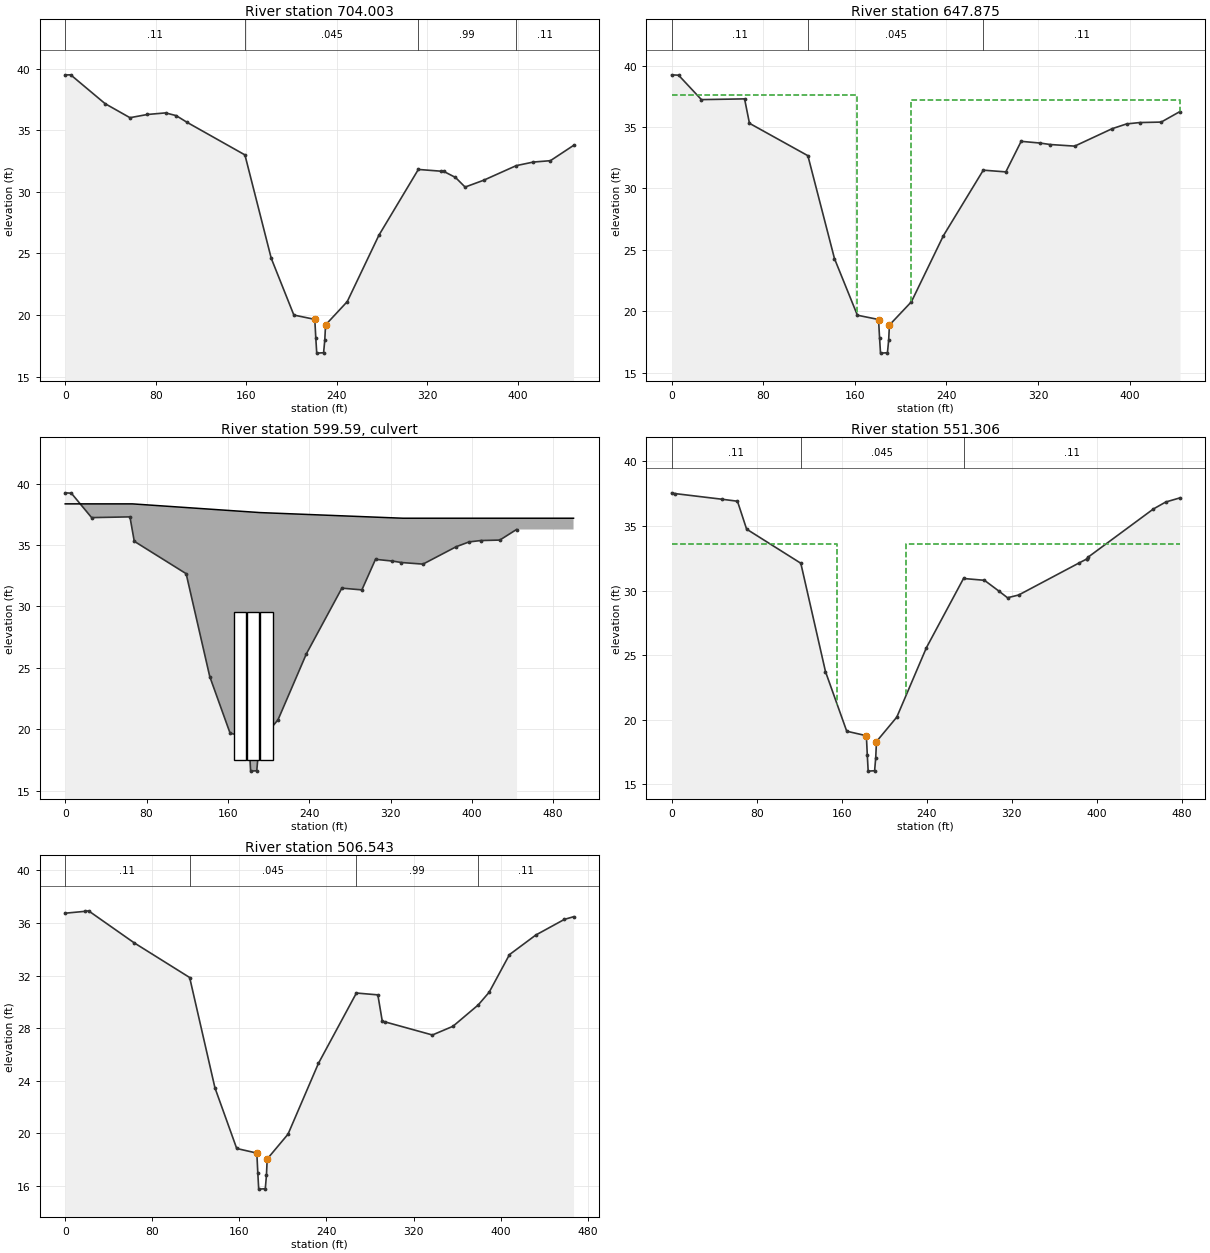
Type RM Length L Ch R = 1 ,704.003 ,54.87,56.13,66.25
BEGIN DESCRIPTION:
443s2u
xsec 4/4 of wherry dr.
Bank Station offset =      4778
END DESCRIPTION:
XS GIS Cut Line= 4
     3208670.265    13904439.232     3208615.191    13904508.659
     3208608.786    13904737.802     3208621.219    13904868.382
#Sta/Elev= 29
       0   39.48    4.85   39.49   35.23   37.15   57.21   36.01   72.51   36.27
   88.62    36.4   97.99   36.18  107.72   35.63  158.75   32.99  181.99    24.6
  201.98   19.99  220.47   19.64  221.35   18.14  222.18    16.9  228.24   16.93
  229.29   17.95  229.98   19.19  249.12   21.08  277.04   26.46  311.93   31.81
  331.63   31.67   334.4   31.65  344.74   31.16  353.24   30.38  369.53   30.93
  398.44   32.12  413.53   32.41  428.58   32.52  449.02   33.76
#Mann= 4 ,-1 , 0
       0     .11       0  158.75    .045       0  311.93     .99       0
  398.44     .11       0
Bank Sta=220.47,229.98
XS Rating Curve= 0
Exp/Cntr=.5,.3

Type RM Length L Ch R = 1 ,647.875 ,96.34,96.57,111.44
BEGIN DESCRIPTION:
copy of 443s2u
inverts adjusted based on slope between 443s3u and 443s2u
xsec 3/4 of wherry dr.
Bank Station offset =      4818
END DESCRIPTION:
XS GIS Cut Line= 6
     3208625.306    13904435.145     3208577.658    13904518.337
     3208571.754    13904557.473     3208568.751    13904609.426
     3208565.001     13904674.29     3208588.522    13904864.295
#Sta/Elev= 27
       0   39.26    6.04   39.23   25.97   37.24   63.67    37.3   67.92   35.31
  118.95   32.67  142.19   24.28  162.18   19.67  180.67   19.32  181.55   17.82
  182.38   16.58  188.44   16.61  189.49   17.63  190.18   18.87  209.32   20.76
  237.24   26.14  272.13   31.49  291.83   31.35  305.21   33.84  321.73    33.7
  330.64   33.58  351.96   33.45  384.65   34.87   397.3   35.26  408.71   35.37
  427.53   35.41  443.92   36.27
#Mann= 3 ,-1 , 0
       0     .11       0  118.95    .045       0  272.13     .11       0
#XS Ineff= 2 , 0
       0  162.18   37.65  209.35       0   37.19
Permanent Ineff=
       F       F
Bank Sta=180.67,190.18
XS Rating Curve= 0
Exp/Cntr=.5,.3

Type RM Length L Ch R = 2 ,599.59  ,,,
BEGIN DESCRIPTION:
443s2; Wherry Drive
END DESCRIPTION:
Bridge Culvert--1,0,-1,-1, 0
Deck Dist Width WeirC Skew NumUp NumDn MinLoCord MaxHiCord MaxSubmerge Is_Ogee
34.785,27,2.6,0, 5, 5, , , .95, 0, 0,0,,
       0   66.05  191.69  332.26     500
   38.36   38.36   37.65   37.19   37.19
                                        
       0   69.05  194.69  335.26     500
   38.36   38.36   37.65   37.19   37.19
                                        
Multiple Barrel Culv=2,12,12,60,.012,.5,1,8,2,17.51,17.55, 3,Culvert #1  , 0 ,18.28
     172     175     185     188     198     201
Culvert Bottom n=.012
BC Design=,, 0 ,, 0 ,,,,,,

Type RM Length L Ch R = 1 ,551.306 ,44.91,44.76,44.22
BEGIN DESCRIPTION:
copy of 443s2u
inverts adjusted based on slope between 443s3u and 443s2u
xsec 2/4 of wherry dr.
Bank Station offset =      4815
END DESCRIPTION:
XS GIS Cut Line= 6
     3208547.651    13904398.361     3208485.358    13904510.742
     3208481.462    13904540.514     3208477.376    13904615.321
     3208476.595    13904676.065     3208486.344    13904860.207
#Sta/Elev= 28
       0   37.56    3.27    37.5   47.75   37.06   61.94   36.91   70.55   34.75
  121.58   32.11  144.82   23.72  164.81   19.11   183.3   18.76  184.18   17.26
  185.01   16.02  191.07   16.05  192.12   17.07  192.81   18.31  211.95    20.2
  239.87   25.58  274.76   30.93  294.46   30.79  307.84   29.97  316.18   29.44
  326.64   29.65  383.51   32.13  390.58   32.43  391.05   32.47  392.37    32.6
  453.52   36.31  465.17   36.85  478.58   37.17
#Mann= 3 ,-1 , 0
       0     .11       0  121.58    .045       0  274.76     .11       0
#XS Ineff= 2 , 0
       0     156    33.6     221       0    33.6
Permanent Ineff=
       F       F
Bank Sta=183.3,192.81
XS Rating Curve= 0
Exp/Cntr=.5,.3

Type RM Length L Ch R = 1 ,506.543 ,278.71,276.7,274.16
BEGIN DESCRIPTION:
copy of 443s2u
inverts adjusted based on slope between 443s3u and 443s2u
xsec 1/4 of wherry dr.
Bank Station offset =      4822
END DESCRIPTION:
XS GIS Cut Line= 5
     3208490.431    13904394.274     3208439.022    13904496.711
     3208437.062    13904530.615     3208430.445    13904675.481
     3208412.775    13904847.946
#Sta/Elev= 27
       0   36.74   18.03   36.88   21.45   36.92   63.29   34.49  114.32   31.85
  137.56   23.46  157.55   18.85  176.04    18.5  176.92      17  177.75   15.76
  183.81   15.79  184.86   16.81  185.55   18.05  204.69   19.94  232.61   25.32
   267.5   30.67   287.2   30.53  291.26   28.53  293.59   28.48  337.31   27.48
  356.18   28.14  379.35   29.76  389.45   30.73   408.1   33.59  432.31   35.08
  458.58   36.27  466.96   36.47
#Mann= 4 ,-1 , 0
       0     .11       0  114.32    .045       0   267.5     .99       0
  379.35     .11       0
Bank Sta=176.04,185.55
XS Rating Curve= 0
Exp/Cntr=.3,.1