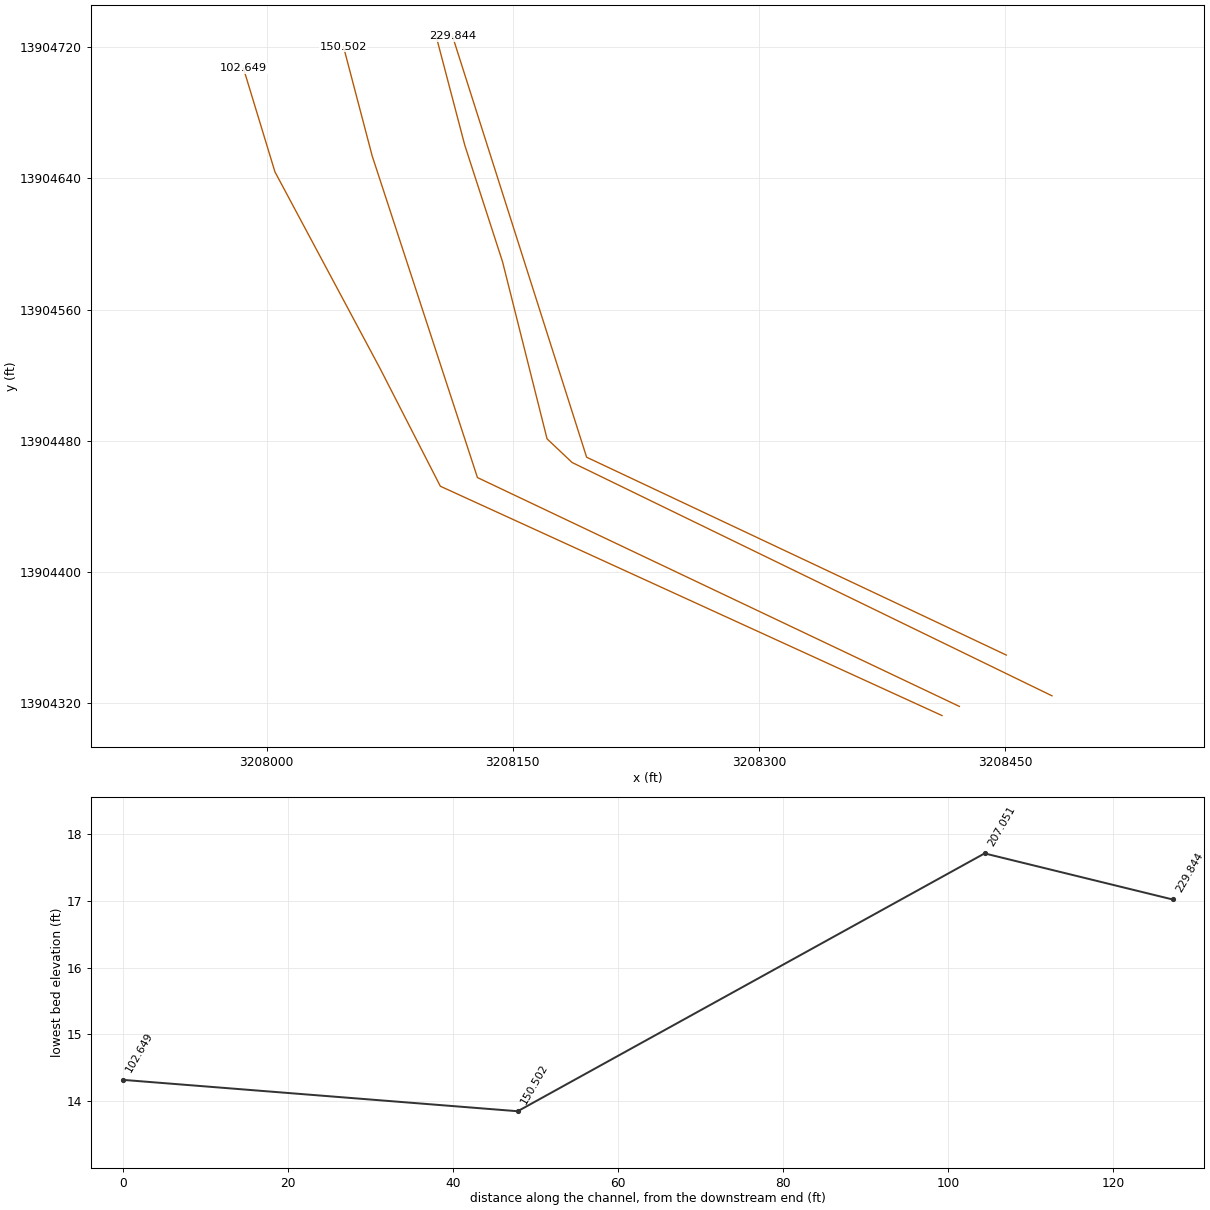
HEC-RAS study R102-03-00.prj: R102-03-00

--- R102-03-00.g03 (geometry) --- (continued)

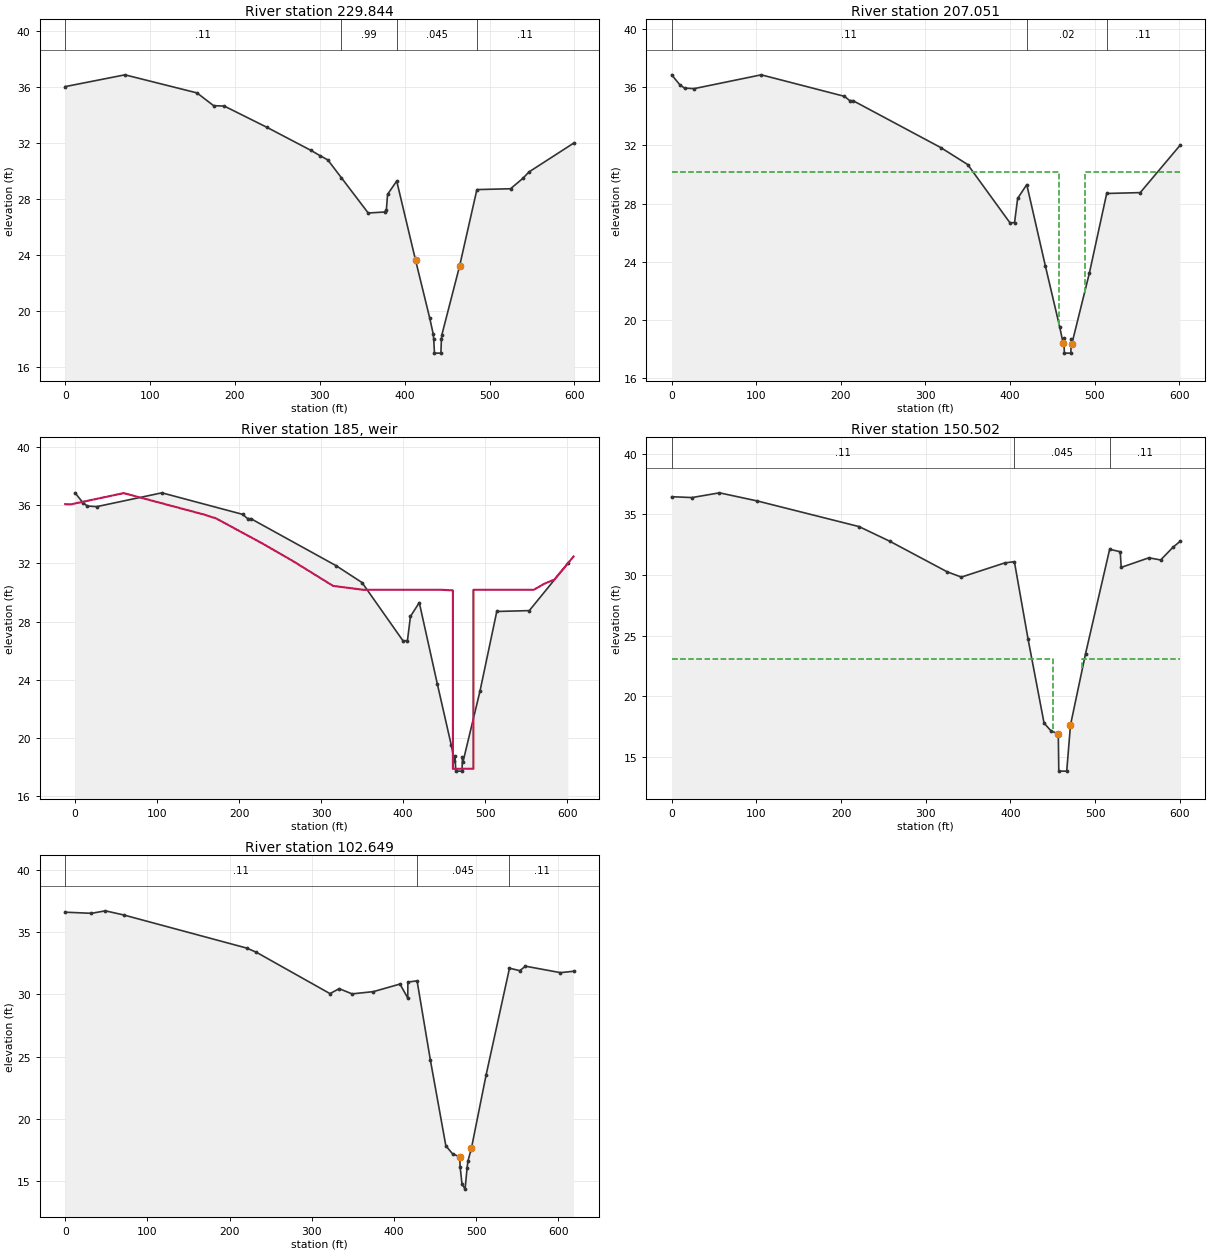
Type RM Length L Ch R = 1 ,229.844 ,17.79,22.79,34.19
BEGIN DESCRIPTION:
443s1u
xsec 4/4 at Energy Dissipater / Grade Control Structure 443s1, surveyed.
Bank Station offset =      4565
END DESCRIPTION:
XS GIS Cut Line= 4
     3208450.728    13904349.435  3208410.73075613904368.3539182
        3208195.       13904470.       3208113.3      13904726.5
#Sta/Elev= 29
       0   36.04    70.4   36.88   155.3   35.59  174.86   34.68  187.49   34.65
  237.84   33.13  289.82   31.48  300.61    31.1  309.43   30.81  325.27   29.55
  357.06   27.02  376.33   27.09   378.4    27.2  379.86   28.35  390.63    29.3
  412.78   23.67   429.5   19.53  433.57   18.41  434.22   18.04  435.14   17.02
  442.71   17.02   443.3   18.01   443.9   18.34  464.67   23.22  485.12   28.69
  524.77   28.75  539.27   29.49  546.51   29.95     599      32
#Mann= 4 ,-1 , 0
       0     .11       0  325.27     .99       0  390.63    .045       0
  485.12     .11       0
Bank Sta=412.78,464.67
XS Rating Curve= 0
Exp/Cntr=.5,.3

Type RM Length L Ch R = 1 ,207.051 ,57.9,56.55,56.55
BEGIN DESCRIPTION:
copy of 443s1u - elevations adjusted based on slope between adjacent dissipater base elevation and u/s xs 4/4.
xsec 3/4 at Energy Dissipater / Grade Control Structure 443s1. Ineffective elevations based on top of concrete wall elevations at upstream end of dissipater structure.  Ineffective stations based on 1:1 contraction to inside edge of concrete walls of structure. Set RS 207 channel n value to 0.02 to remove nonconverging weir sol'n message.
Bank Station offset =    4536
END DESCRIPTION:
XS GIS Cut Line= 6
     3208478.591    13904324.596      3208186.15    13904466.778
     3208170.887    13904481.193     3208143.782    13904589.038
      3208120.75    13904660.141       3208103.3    13904726.582
#Sta/Elev= 26
       0   36.85    9.89   36.15   15.16   35.94   26.46    35.9  105.87   36.85
  204.26   35.37  210.37   35.08  214.44   35.07  317.96   31.85  349.89   30.68
  399.89   26.67  405.28   26.69  408.92   28.35  419.69    29.3  441.84   23.67
  458.56   19.53  462.63   18.41  463.28   18.73   464.2   17.71  471.77   17.71
  472.36    18.7  472.96   18.34  493.73   23.22  514.18   28.69  553.83   28.75
  600.82      32
#Mann= 3 ,-1 , 0
       0     .11       0  419.69     .02       0  514.18     .11       0
#XS Ineff= 2 , 0
       0     458   30.14     488       0   30.18
Permanent Ineff=
       F       F
Bank Sta=462.63,472.96
XS Rating Curve= 0
Exp/Cntr=.5,.3

Type RM Length L Ch R = 5 ,185     ,,,
BEGIN DESCRIPTION:
Energy Dissipater / Grade Control Structure, 443s1, at RS 185, modeled as inline weir.  Used 2.8 for weir coefficient based on PMT guidance recommendations, structure geometry (flat u/s and d/s slope of ~ 4H:1V), and comparison to weir coefficients for various geometries listed in Tables 5-4 to 5-13 (pp. 5-40 to 5-44) in "Handbook of Hydraulics", 6th Edition (1976), Brater, E.F., and King, H.W.  McGraw-Hill, Inc., New York, N.Y.  Set RS 207 channel n value to 0.02 to remove nonconverging weir sol'n message.
END DESCRIPTION:
IW Pilot Flow=0
#Inline Weir SE= 27
     -12   36.07   -5.76   36.05   59.39   36.83  156.33   35.37  166.12   35.19
  170.99   35.12  228.92   33.35  265.27   32.17  306.24   30.74  314.51   30.45
  351.43   30.18  366.29   30.18  391.98   30.18  400.84   30.18  414.33   30.18
   425.1   30.18  447.25   30.18   460.7   30.14   460.7   17.87  485.69   17.87
   485.7   30.18  499.14   30.18  519.59   30.18  559.24   30.18  571.57   30.58
  584.48   30.89  607.76   32.47
IW Dist,WD,Coef,Skew,MaxSub,Min_El,Is_Ogee,SpillHt,DesHd
5,44,3,0,.95,, 0 ,,,2.5,2.5,

Type RM Length L Ch R = 1 ,150.502 ,41.8,47.85,51.86
BEGIN DESCRIPTION:
Copy of 443v1 - elevations adjusted as necessary
xsec 2/4 at Energy Dissipater / Grade Control Structure 443s1.  Ineffective elevations based on top of concrete wall elevations at downstream end of dissipater structure.  Ineffective stations based on 1:1 expansion from inside edge of concrete walls of structure.
Bank offset =   4537
END DESCRIPTION:
XS GIS Cut Line= 4
     3208422.131    13904318.149     3208128.474    13904457.599
     3208064.297    13904653.695     3208046.849    13904720.136
#Sta/Elev= 25
       0   36.45   23.92   36.38   56.43   36.77  101.11    36.1  221.19   33.99
  257.57   32.78  325.09   30.27  342.03   29.83  393.34      31  404.59    31.1
  420.71   24.74  439.62   17.81  447.72   17.17  456.43   16.92  457.02   13.85
  466.39   13.85  470.81   17.64  488.64   23.53  517.06   32.12  529.54   31.92
  530.72   30.63   563.4   31.42  577.26   31.24  591.58   32.27  600.11   32.77
#Mann= 3 ,-1 , 0
       0     .11       0  404.59    .045       0  517.06     .11       0
#XS Ineff= 2 , 0
       0     450   23.05     485       0   23.08
Permanent Ineff=
       F       F
Bank Sta=456.43,470.81
XS Rating Curve= 0
Exp/Cntr=.5,.3

Type RM Length L Ch R = 1 ,102.649 ,108.66,102.65,98.31
BEGIN DESCRIPTION:
443v1
xsec 1/4 at Energy Dissipater / Grade Control Structure 443s1.
Bank Station offset =      4513
END DESCRIPTION:
XS GIS Cut Line= 5
      3208411.56    13904312.571     3208105.861    13904452.314
     3208069.036    13904524.242     3208005.075    13904643.874
     3207985.848    13904707.079
#Sta/Elev= 30
       0   36.63   31.92   36.54   48.89   36.74      71   36.41  220.84   33.74
  232.73    33.4  322.27   30.07  333.43   30.47   349.1   30.05  375.01   30.23
  407.43   30.84  416.93   29.71  416.99      31  428.24    31.1  444.36   24.74
  463.27   17.81  471.37   17.17  480.08   16.92  480.67    16.1  482.88   14.74
  486.65   14.32  489.09   16.01  490.04   16.55  494.46   17.64  512.29   23.53
  540.71   32.12  553.19   31.92  560.16   32.28  602.72   31.76  618.65   31.87
#Mann= 3 ,-1 , 0
       0     .11       0  428.24    .045       0  540.71     .11       0
Bank Sta=480.08,494.46
XS Rating Curve= 0
Exp/Cntr=.3,.1

Chan Stop Cuts=-1